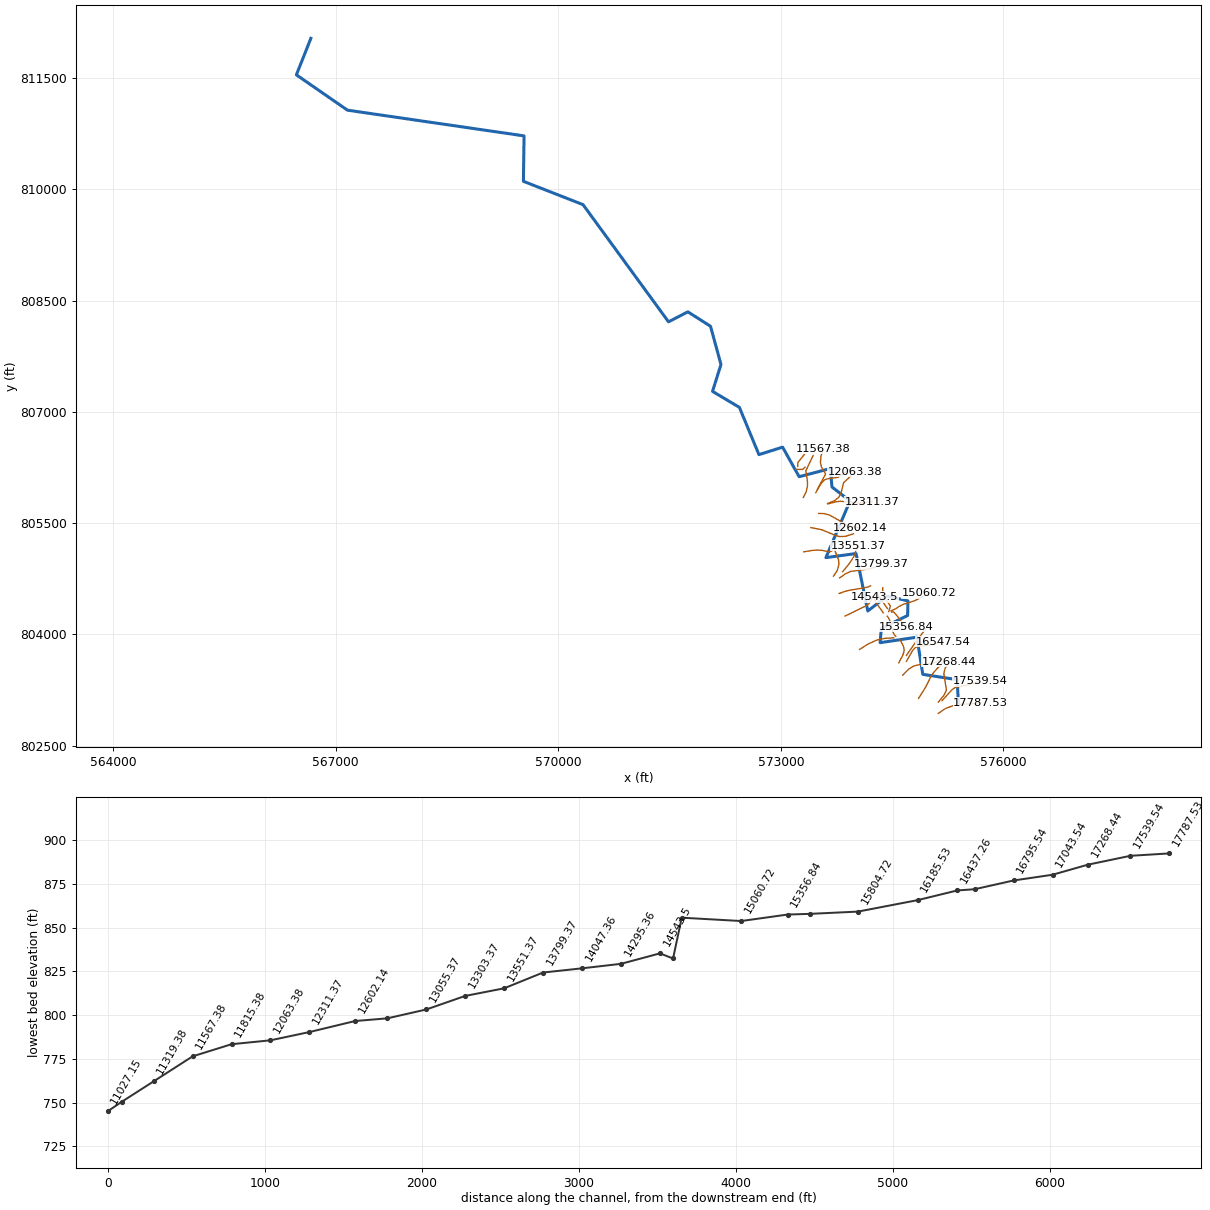
--- 11111_ras.prj (project) ---

Proj Title=11111
Current Plan=p01
Default Exp/Contr=0.3,0.1
English Units
Geom File=g01
Flow File=f01
Plan File=p01
Y Axis Title=Elevation
X Axis Title(PF)=Main Channel Distance
X Axis Title(XS)=Station
BEGIN DESCRIPTION:
RFD model 11111 exported to HEC-RAS
END DESCRIPTION:

--- 11111_ras.p01 (plan) ---

Plan Title=Plan 01
Program Version=4.10
Short Identifier=Plan 01
Geom File=g01
Flow File=f01
Subcritical Flow
Calc Critical at every XS
Secant Critical Depth

--- 11111_ras.f01 (steady flow) ---

Flow Title=Flow 01
Program Version=5.01
Number of Profiles= 6
Profile Names=10yr,25yr,50yr,100yr,100plus,500yr
River Rch & RM=11111,54,17787.53
  960.71 1576.41 2166.74 2717.03 3966.86 5508.31
River Rch & RM=11111,54,17539.54
  965.65 1584.66 2178.21 2731.55 3988.06 5534.15
River Rch & RM=11111,54,17268.44
  971.09 1593.73 2190.82  2747.5 4011.36 5562.51
River Rch & RM=11111,54,17043.54
 1034.67 1699.36 2337.29 2932.37 4281.26 5887.25
River Rch & RM=11111,54,16795.54
  1039.3 1707.08 2348.03 2945.96 4301.09 5911.17
River Rch & RM=11111,54,16547.54
 1054.67  1732.7 2383.64 2990.99 4366.85 5990.18
River Rch & RM=11111,54,16185.53
 1060.29 1742.06 2396.64 3007.43 4390.84 6018.93
River Rch & RM=11111,54,15804.72
 1071.37 1760.47 2422.18 3039.65 4437.89 6075.02
River Rch & RM=11111,54,15500.72
 1074.08 1764.97 2428.42 3047.52 4449.38 6088.69
River Rch & RM=11111,54,15356.84
 1075.79 1767.82 2432.37 3052.51 4456.67 6097.39
River Rch & RM=11111,54,15060.72
 1077.73 1771.05 2436.86  3058.2 4464.97 6107.33
River Rch & RM=11111,54,14682.36
  1106.6 1819.14 2503.67 3142.65 4588.27 6254.38
River Rch & RM=11111,54, 14543.5
 1108.32 1821.99 2507.62 3147.63 4595.53 6262.99
River Rch & RM=11111,54,14295.36
 1109.54 1824.02 2510.43 3151.18 4600.72 6269.13
River Rch & RM=11111,54,14047.36
 1134.64 1865.71 2568.26 3224.16 4707.28 6395.21
River Rch & RM=11111,54,13799.37
 1138.04 1871.37 2576.11 3234.06 4721.73 6412.27
River Rch & RM=11111,54,13551.37
 1141.22 1876.63  2583.4 3243.26 4735.16 6428.09
River Rch & RM=11111,54,13303.37
 1144.38 1881.89 2590.68 3252.45 4748.57  6443.9
River Rch & RM=11111,54,13055.37
 1147.06 1886.33 2596.84 3260.22 4759.92 6457.27
River Rch & RM=11111,54,12807.37
 1149.02 1889.58 2601.35 3265.89  4768.2 6466.98
River Rch & RM=11111,54,12602.14
 1178.09 1937.86 2668.28 3350.35 4891.51 6612.02
River Rch & RM=11111,54,12311.37
 1181.51 1943.52 2676.12 3360.22 4905.92 6628.86
River Rch & RM=11111,54,12063.38
 1246.41 2051.07 2825.05 3547.89 5179.92 6948.06
River Rch & RM=11111,54,11815.38
 1264.37 2080.76  2866.1 3599.55 5255.34 7035.18
River Rch & RM=11111,54,11567.38
 1271.39 2092.37 2882.16 3619.76 5284.84 7069.21
River Rch & RM=11111,54,11319.38
 1275.24 2098.74 2890.97 3630.86 5301.05 7087.95
River Rch & RM=11111,54,11117.35
 1275.72 2099.53 2892.07 3632.25 5303.08  7090.3
River Rch & RM=11111,54,10997.43
 1280.31 2107.13 2902.58 3645.46 5322.38 7112.53
River Rch & RM=11111,54,10838.52
 1281.54 2109.15 2905.37 3648.97 5327.49 7118.37
River Rch & RM=11111,54,10617.66
 1285.71 2116.01 2914.83 3660.85 5344.84 7138.24
River Rch & RM=11111,54,10449.58
 1287.19 2118.44 2918.18 3665.05 5350.98 7145.24
River Rch & RM=11111,54,10383.23
 1290.38  2123.7 2925.43 3674.15 5364.25 7160.41
River Rch & RM=11111,54,10134.66
 1293.33 2128.55 2932.12 3682.54 5376.51  7174.4
River Rch & RM=11111,54,9886.656
  1295.3 2131.79 2936.58 3688.14 5384.69 7183.72
River Rch & RM=11111,54,9638.095
 1351.43 2224.31 3064.27 3848.52 5618.83 7450.86
River Rch & RM=11111,54,9433.895
 1356.33 2232.35 3075.34  3862.4 5639.11 7473.81
River Rch & RM=11111,54,9129.755
 1695.43 2792.47 3849.54 4835.97 7060.52 9068.07
River Rch & RM=11111,54,8881.756
 1696.36    2794 3851.65 4838.62 7064.39 9072.32
River Rch & RM=11111,54,8633.758
 1698.92 2798.22 3857.47 4845.92 7075.04    9084
River Rch & RM=11111,54,8385.759
 1702.41 2803.97 3865.39 4855.86 7089.56 9099.93
River Rch & RM=11111,54,7991.543
 1769.46 2914.49 4017.97 5047.49 7369.33 9406.82
River Rch & RM=11111,54,7838.263
 1773.13 2920.54 4026.32 5057.97 7384.64 9423.58
River Rch & RM=11111,54,7689.763
 1774.06 2922.07 4028.43 5060.61 7388.49 9427.77
River Rch & RM=11111,54,7393.765
 1776.16 2925.51 4033.17 5066.55 7397.17 9437.19
River Rch & RM=11111,54,7145.767
 1778.25 2928.95  4037.9 5072.49 7405.83  9446.6
River Rch & RM=11111,54,6897.769
 2285.25 3758.44 5177.58 6497.12 9485.7911652.24
Boundary for River Rch & Prof#=11111,54,1
Up Type= 0
Dn Type= 2
Boundary for River Rch & Prof#=11111,54,2
Up Type= 0
Dn Type= 2
Boundary for River Rch & Prof#=11111,54,2
Up Type= 0
Dn Type= 2
Boundary for River Rch & Prof#=11111,54,2
Up Type= 0
Dn Type= 2
Boundary for River Rch & Prof#=11111,54,2
Up Type= 0
Dn Type= 2
Boundary for River Rch & Prof#=11111,54,2
Up Type= 0
Dn Type= 2

--- 11111_ras.g01 (geometry) ---

Geom Title=11111
Program Version=4.10

River Reach=11111,54
Reach XY= 30
575394.740082651803050.548793271575376.059857816803389.264257804
574913.642778218803460.837991551574833.453761011803961.833057001
574338.722488225803887.794254094 574353.47270453804080.516614765
574708.677874357804253.872749493574714.037921101804450.361154109
574434.631125957804517.152897015574171.911020488804314.774633139
574013.882142276805089.523777381573607.239763975805034.232086271
573932.107288092805797.705213293 573689.16462037 805986.83021605
573667.484579474806235.334454462573246.772454619 806124.94851011
573023.707886338806523.459586889572704.645418614806422.638738438
572440.955546707807060.137322873572079.188365906807275.158649251
572192.993716329807638.035864457572052.069048256808153.021697909
571746.667812228808347.262962922571485.733467191808212.939637184
570333.832505852 809792.25054355569530.037020087810106.711396188
569538.530740172 810719.29519856567158.448059142811065.788977712
 566469.60783571811542.120536014566664.667002946812034.193005368

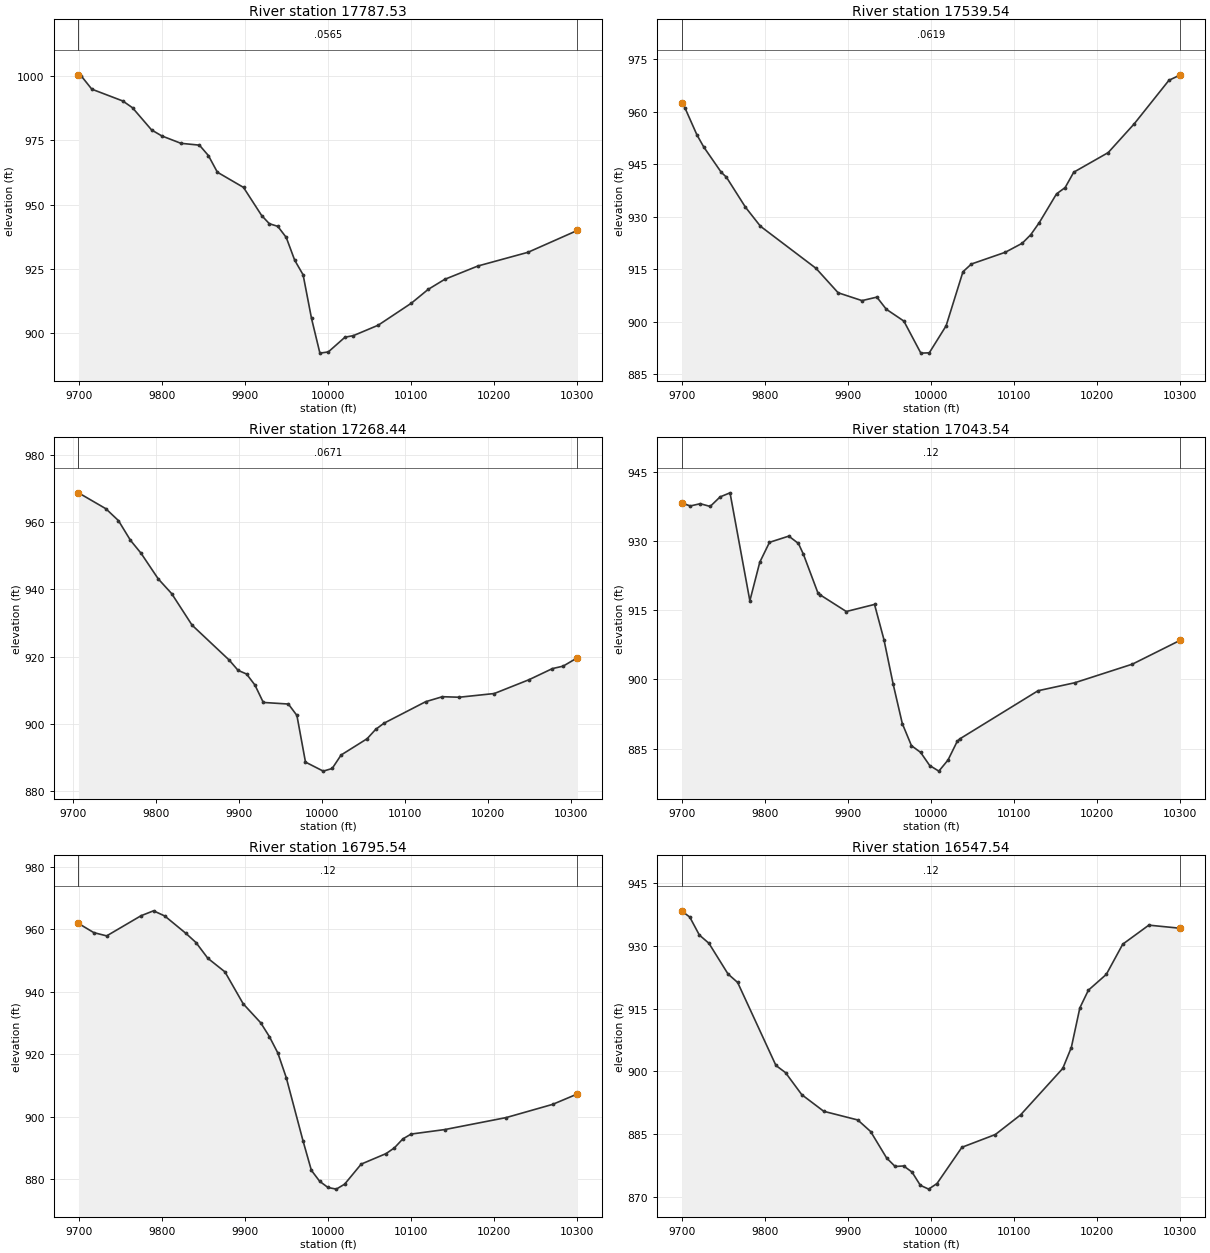
Type RM Length L Ch R = 1 ,17787.53,247.998500,247.998500,247.998500
XS GIS Cut Line= 6
575122.114970001802934.807420145575216.233059974  802998.5123632
575315.950266282803037.124684478575414.321414296803054.152592374
 575583.91017193803064.993745435575694.218103024803078.407210337
#Sta/Elev= 30
9699.0781000.3899702.675  999.849715.143994.82299752.472990.24249764.252987.6051
9787.265978.98769799.594976.66879822.621973.80589844.966973.08719855.784969.0509
9866.597962.59359898.133956.68319920.034945.76849929.269942.59739939.474941.5694
9949.679937.27289959.884928.4269 9970.03922.75899980.159905.85349990.288892.3488
10000.42892.809310020.58898.544810030.61899.131110060.67903.195110100.75911.7708
10120.79917.069110140.83920.991710180.91926.177310241.31 931.49210300.96939.9977
#Mann= 3 , 0 , 0
9699.078  0.0565       09699.078  0.0565       010300.96  0.0565       0
#XS Ineff= 2 , 0
       0                               0
Bank Sta=9699.078,10300.96
Exp/Cntr=0.3,0.1

Type RM Length L Ch R = 1 ,17539.54,271.093900,271.093900,271.093900
XS GIS Cut Line= 6
 575172.28085398803105.482140919575303.619667752803249.433518702
575339.150742861803277.964749119575371.295387673803289.275385211
575525.561226627803320.453931888575688.279559966803368.597248603
#Sta/Elev= 30
9699.076 962.4339703.056961.13359717.691953.31939725.808949.90469746.962942.6574
9753.199941.26019776.232932.66389794.286927.23029861.252915.21999888.022908.2201
 9916.78905.98139934.735906.98059946.078903.52219967.287  900.149987.793890.9778
9997.975891.067810018.28898.787310038.59914.222510048.74916.434210089.64919.7896
10110.17922.380710120.43924.8268 10130.7928.278210151.46936.476810161.85938.2729
10172.24942.668710213.79948.2685 10245.2956.491410287.08968.928510300.98970.4881
#Mann= 3 , 0 , 0
9699.076  0.0619       09699.076  0.0619       010300.98  0.0619       0
#XS Ineff= 2 , 0
       0                               0
Bank Sta=9699.076,10300.98
Exp/Cntr=0.3,0.1

Type RM Length L Ch R = 1 ,17268.44,224.903000,224.903000,224.903000
XS GIS Cut Line= 6
 575123.33579603803087.620870744575195.859508491803175.223873015
575232.200533769803247.225043942575196.924222228803474.458595715
575215.232951208803545.152224129575270.355488482803628.464629378
#Sta/Elev= 30
9706.476968.74589739.437964.02219754.652960.47739769.125954.62059781.833950.7825
9802.644943.12369818.849938.73549843.409929.35939888.181918.95979898.866915.9016
9909.102 914.809 9919.21 911.529  9929.3906.34669959.534905.87069969.813902.4772
9980.157888.587310001.58885.898710012.34886.686210023.09890.694110054.46 895.546
10064.75898.321110074.85900.170710125.05906.567810145.23908.051710165.56907.8976
10207.77908.999310249.62  913.1110277.94916.429910290.77917.149910308.04919.6521
#Mann= 3 , 0 , 0
9706.476  0.0671       09706.476  0.0671       010308.04  0.0671       0
#XS Ineff= 2 , 0
       0                               0
Bank Sta=9706.476,10308.04
Exp/Cntr=0.3,0.1

Type RM Length L Ch R = 1 ,17043.54,247.998400,247.998400,247.998400
XS GIS Cut Line= 6
574856.024965358803136.097446815574951.015506726 803286.94912984
575020.802912005 803427.68172286575044.235400486 803466.62206275
575102.713232438803535.318403563575197.842036785803624.912115035
#Sta/Elev= 30
9699.028 938.2129709.679937.56699721.644938.05339733.608937.46029745.573939.5248
9757.537940.40839781.466917.03189793.431925.38659805.145929.68989828.451931.0354
9840.104929.44119846.141927.0762 9863.41918.81489865.618918.39179897.822 914.712
9931.872916.24579943.222908.62849954.367898.97169965.386890.44079976.404885.6667
9987.423884.21999998.442881.361310009.46880.153210020.49882.549110031.53886.5706
10034.49887.108710129.09897.556210173.44899.287910242.98903.320210300.93 908.512
#Mann= 3 , 0 , 0
9699.028    0.12       09699.028    0.12       010300.93    0.12       0
#XS Ineff= 2 , 0
       0                               0
Bank Sta=9699.028,10300.93
Exp/Cntr=0.3,0.1

Type RM Length L Ch R = 1 ,16795.54,247.998500,247.998500,247.998500
XS GIS Cut Line= 6
574642.645765292803449.667229541574724.018703989803532.454757285
574791.300148213803572.588077085574853.561109185803589.169946436
575034.854911984803606.697596603575181.595367689803669.198819362
#Sta/Elev= 30
9699.152961.81929717.651958.87949733.186957.84399774.602964.2873 9789.66965.8531
9803.185964.20869828.709958.65059840.846955.72399855.167950.68219875.775 946.343
9897.828 936.1219918.892930.07529929.355925.65959939.553920.42699949.751912.5208
9969.979892.29639980.031882.89869990.076879.376210000.09877.4004 10010.1876.8781
10020.12878.457610040.14884.876210070.18888.243310080.19890.070810090.27892.9136
10100.35894.481710141.03895.9252   10215899.7526 10271.1903.980710300.95907.3115
#Mann= 3 , 0 , 0
9699.152    0.12       09699.152    0.12       010300.95    0.12       0
#XS Ineff= 2 , 0
       0                               0
Bank Sta=9699.152,10300.95
Exp/Cntr=0.3,0.1

Type RM Length L Ch R = 1 ,16547.54,110.278400,110.278400,110.278400
XS GIS Cut Line= 6
574692.502113912803636.380893232 574778.85569267803786.033647094
574817.293049398 803825.21199425574856.424120913 803837.81314781
575032.066198627803859.280197638575181.406421488803901.448050077
#Sta/Elev= 30
9699.208 938.3189709.159936.82649720.704932.5433 9732.25930.5748 9755.34923.2248
9766.886921.22429813.067 901.4069824.613899.69699844.265894.42699870.794890.4585
9911.758888.39499927.272885.63589946.564879.31869956.833877.28869967.102877.4179
9977.178875.95819987.221872.79719997.264871.884310007.29873.219110037.39 881.874
10077.66884.915510108.09889.6026   10159900.7014 10169.3905.689410179.59915.1535
10189.89919.375810211.49923.144510231.34930.360610262.78   934.910300.93934.1514
#Mann= 3 , 0 , 0
9699.208    0.12       09699.208    0.12       010300.93    0.12       0
#XS Ineff= 2 , 0
       0                               0
Bank Sta=9699.208,10300.93
Exp/Cntr=0.3,0.1

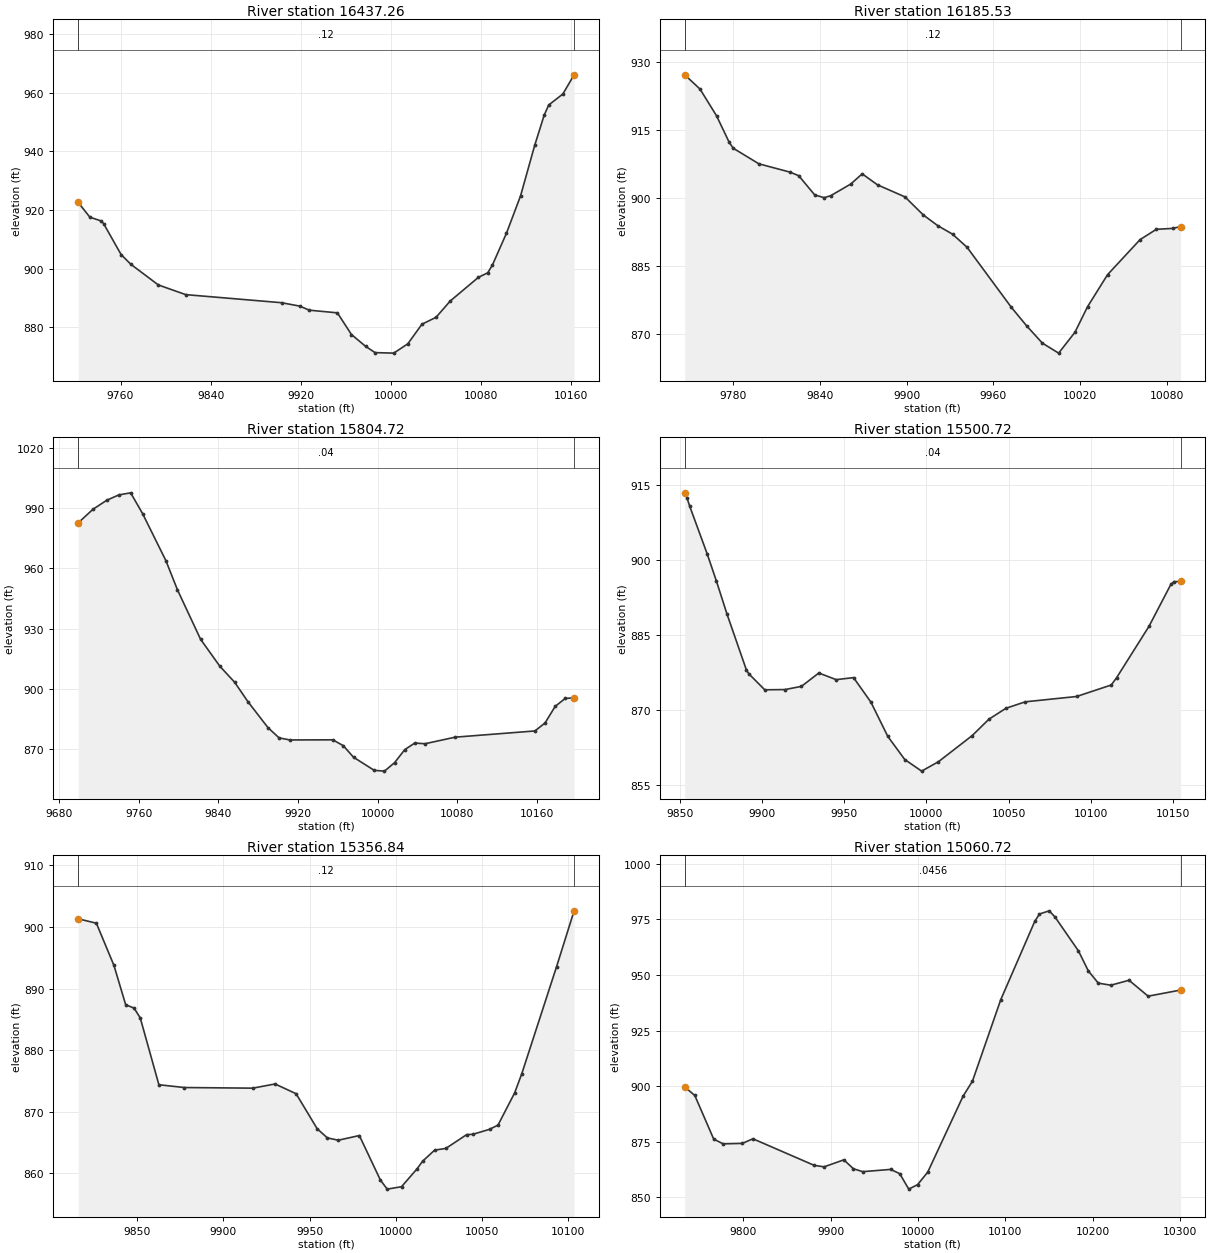
Type RM Length L Ch R = 1 ,16437.26,251.733200,251.733200,251.733200
XS GIS Cut Line= 4
574693.396694899803716.465373307574804.287290573 803877.43559286
574815.018638551803891.744056806574950.949046165804072.984600306
#Sta/Elev= 30
9722.483922.57759732.847917.55089742.936916.2674 9744.99915.38479760.564904.7892
9769.276901.46239793.563894.44619817.849891.14479902.851 888.387 9919.14 887.219
9927.408885.84139952.408 884.9329964.908877.52219977.408873.51959985.807871.3677
10002.41871.191410014.91874.381110027.41881.055610039.91 883.40210052.47888.9514
10077.41897.008610085.81 898.60510089.91901.224510102.41912.099910114.91924.8371
10127.41942.008110135.81952.298310139.91955.836410152.41959.555510162.39 966.108
#Mann= 3 , 0 , 0
9722.483    0.12       09722.483    0.12       010162.39    0.12       0
#XS Ineff= 2 , 0
       0                               0
Bank Sta=9722.483,10162.39
Exp/Cntr=0.3,0.1

Type RM Length L Ch R = 1 ,16185.53,380.811900,380.811900,380.811900
XS GIS Cut Line= 6
574590.185494334803615.783552513574642.808654308803717.496631488
574657.596628457803760.474529877574662.000008225803794.902398467
574652.209160298803839.333194777574605.706862241803929.931326777
#Sta/Elev= 30
9746.889927.20329757.426 924.0599768.859918.13859777.453912.36469780.292910.9869
9798.084907.52729819.589905.68689825.567904.90459836.616900.65379843.107900.0377
9847.664900.47649861.471903.05019869.406905.30869879.982902.87639898.941 900.215
9911.546 896.2319921.724893.81789931.758891.97839941.791889.07919972.421875.7802
9982.877 871.7259993.783867.883710005.03865.670510016.29870.284510024.96875.9224
10038.79883.014610061.25890.769510072.48893.043810083.71893.249810089.24893.6452
#Mann= 3 , 0 , 0
9746.889    0.12       09746.889    0.12       010089.24    0.12       0
#XS Ineff= 2 , 0
       0                               0
Bank Sta=9746.889,10089.24
Exp/Cntr=0.3,0.1

Type RM Length L Ch R = 1 ,15804.72,303.999900,303.999900,303.999900
XS GIS Cut Line= 6
574061.127403826803796.793731377574181.634346962803872.415724963
574288.987755984803920.546158746574340.688859016803934.596523196
574406.899957687803946.116763175574523.828279734803953.006013528
#Sta/Elev= 30
9699.067982.57289713.885989.32289727.739993.80449739.749996.45249751.759997.5116
9763.769987.19299787.237963.74739798.849 949.2499822.073924.68529841.388911.3033
 9856.31903.31279869.688 893.6279889.804880.74559900.969875.64439911.885 874.609
9954.862874.67719965.402871.81239975.806866.02379996.616859.496410006.91859.1076
10017.11863.336310027.27869.778610037.42873.082610047.57872.723510078.02875.9983
10158.16879.090510168.35883.084610178.53891.327210188.65895.275810197.51895.5439
#Mann= 3 , 0 , 0
9699.067    0.04       09699.067    0.04       010197.51    0.04       0
#XS Ineff= 2 , 0
       0                               0
Bank Sta=9699.067,10197.51
Exp/Cntr=0.3,0.1

Type RM Length L Ch R = 1 ,15500.72,143.876200,143.876200,143.876200
XS GIS Cut Line= 6
574432.610461789804244.881976936574449.003199893804225.548578564
574468.822844732804186.509384531574511.554157811804031.846183274
574528.129083621803995.149452675574549.027306877803973.327809616
#Sta/Elev= 30
9852.993913.43639854.384912.40419856.058910.72469866.564901.31059872.169895.9003
9878.619889.28679890.449878.09569891.866877.31149901.664874.07359913.956874.1195
9923.995874.76039934.559877.43199945.123876.10279955.687876.50639966.251871.6098
 9976.55864.75039986.843860.1429 9997.12857.821510007.37859.708910027.86864.9214
10038.11868.216310048.41870.381310060.17871.672910091.39872.735710112.48875.0357
10115.68876.4667 10135.4886.742210148.75895.1493 10150.6895.680110154.67895.7234
#Mann= 3 , 0 , 0
9852.993    0.04       09852.993    0.04       010154.67    0.04       0
#XS Ineff= 2 , 0
       0                               0
Bank Sta=9852.993,10154.67
Exp/Cntr=0.3,0.1

Type RM Length L Ch R = 1 ,15356.84,296.119200,296.119200,296.119200
XS GIS Cut Line= 6
 574494.65232328804300.125281559574511.096088357804303.315594021
574521.654766888804301.090379396574570.070707821 804245.58039243
574649.181106388804137.131099442574690.020908134804105.041524764
#Sta/Elev= 30
9815.707901.33139826.248900.61519836.447893.75369843.248887.3725 9848.08886.8317
9851.689885.24559862.524874.37549877.373873.92489916.961873.82329929.902874.5046
9942.132872.92019954.363867.22819960.259865.74849966.593865.36689978.824866.1277
9991.055858.88719994.996857.423410003.29857.816610012.36 860.73910015.51861.9553
10022.51863.757910029.01864.035910041.06866.272210044.71  866.3310054.37867.1377
10059.28867.827610068.92 873.04710073.04876.144310093.28893.578610103.42902.6265
#Mann= 3 , 0 , 0
9815.707    0.12       09815.707    0.12       010103.42    0.12       0
#XS Ineff= 2 , 0
       0                               0
Bank Sta=9815.707,10103.42
Exp/Cntr=0.3,0.1

Type RM Length L Ch R = 1 ,15060.72,378.364900,378.364900,378.364900
XS GIS Cut Line= 6
574484.308685213804317.221370772574541.308772504804340.450898752
 574583.36936897804369.108132318574649.441956222804404.371655136
574806.662364721804454.119771108574997.615517139804553.480367303
#Sta/Elev= 30
9732.746899.70239744.291895.83149765.888876.25529776.687874.07639798.765874.2847
9810.865876.36199881.047864.41389892.382863.73869915.052866.88739926.024862.8635
9936.704 861.5719968.747862.58549979.131860.64879989.421853.71379999.558855.7422
10011.23861.399910051.69895.5557 10062.4902.259910094.84938.922510133.79974.1287
10139.22977.458410150.32978.886910156.88976.185410183.84960.869910195.25951.8184
10206.66946.357710221.03945.430510241.79947.662110263.71940.501710300.93943.2607
#Mann= 3 , 0 , 0
9732.746  0.0456       09732.746  0.0456       010300.93  0.0456       0
#XS Ineff= 2 , 0
       0                               0
Bank Sta=9732.746,10300.93
Exp/Cntr=0.3,0.1

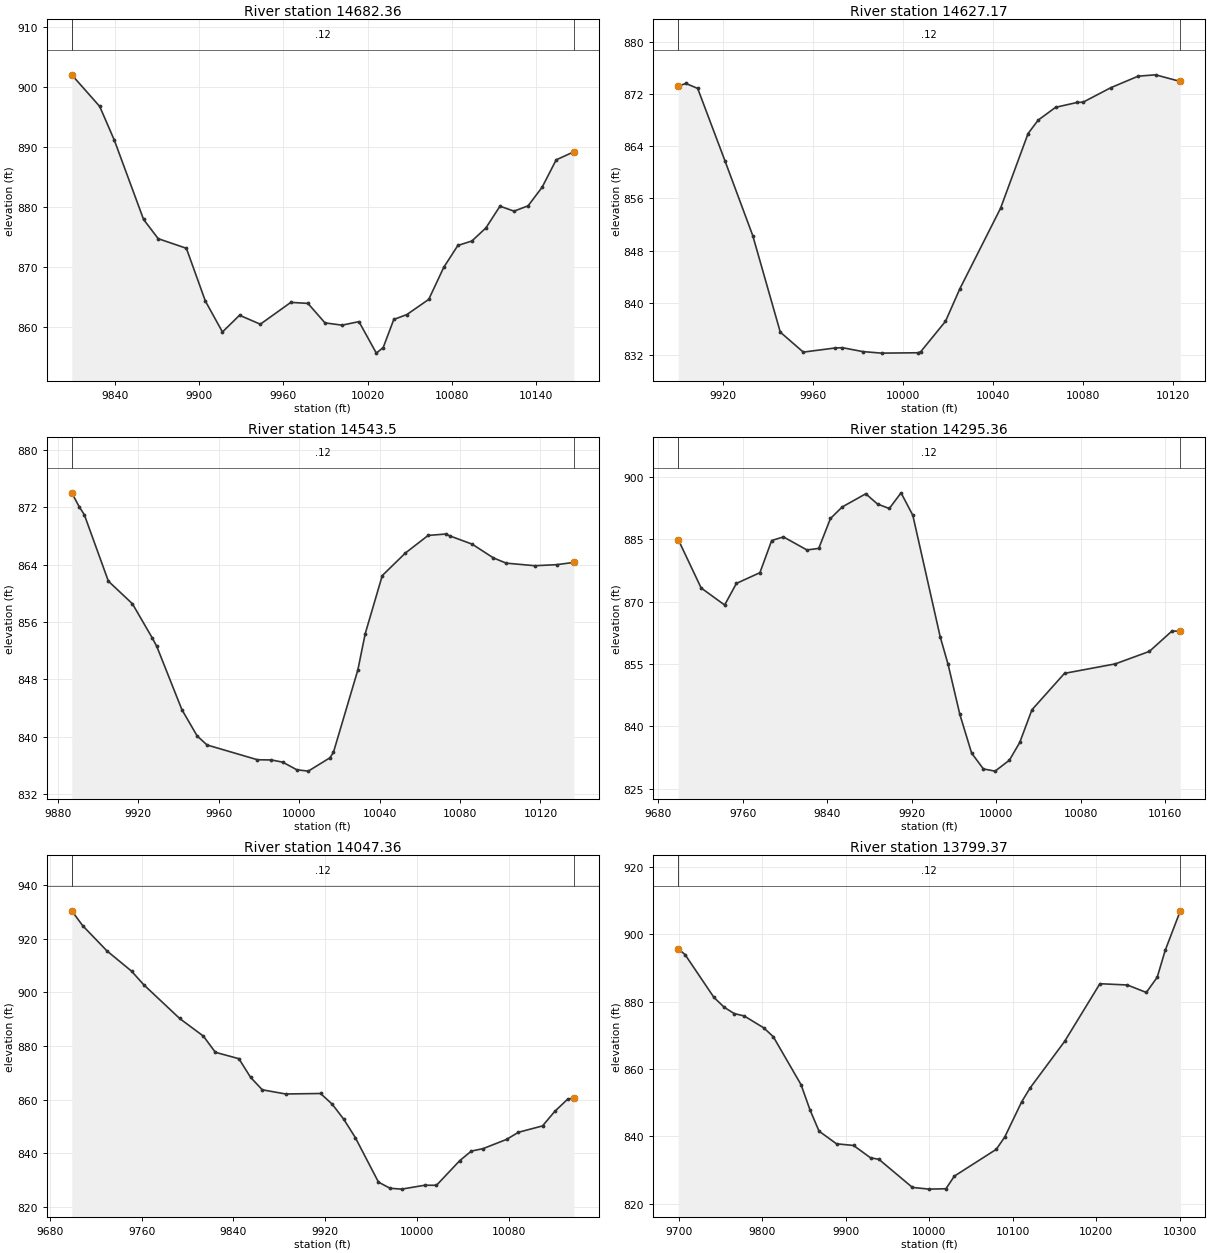
Type RM Length L Ch R = 1 ,14682.36,55.185800,55.185800,55.185800
XS GIS Cut Line= 5
574454.392263398804305.904809974574476.436460957804381.834823765
574398.873543635804493.688715063574373.563539043804527.979689024
574373.563539043804627.586803891
#Sta/Elev= 30
9809.316902.0439  9829.2896.77299839.613891.14239860.438877.92189870.851 874.717
9890.902873.11399904.402864.32169916.571859.1595 9928.74861.94339943.549860.4552
9965.247 864.0929977.416863.92449989.585860.671710001.75860.291810013.74 860.883
10026.13855.628710031.02 856.56710038.55861.243210047.86862.061410063.41864.5901
10074.14869.949610084.14873.583810094.14874.330110104.14876.515810114.14880.1362
10124.14879.307710134.14880.196710144.14883.296510154.14887.861210166.72889.2075
#Mann= 3 , 0 , 0
9809.316    0.12       09809.316    0.12       010166.72    0.12       0
#XS Ineff= 2 , 0
       0                10016.69       0
Bank Sta=9809.316,10166.72
Exp/Cntr=0.3,0.1

Type RM Length L Ch R = 1 ,14627.17,83.669500,83.669500,83.669500
XS GIS Cut Line= 2
574436.949163854804347.936132684 574308.68440184804530.288444936
#Sta/Elev= 25
9900.173 873.1929903.561873.61439908.809872.85119920.943 861.7469933.261850.3196
9945.487835.53989955.706832.4795 9969.94833.11549973.087833.15449982.166832.5579
9990.469832.323110006.62832.379110007.85 832.54110018.84837.190210025.23842.1766
 10043.3 854.50310055.52865.9464   10060867.997110067.75869.958110077.38870.7103
10079.97870.7466 10092.2872.952610104.43874.729510112.14874.932710123.12873.9148
#Mann= 3 , 0 , 0
9900.173    0.12       09900.173    0.12       010123.12    0.12       0
#XS Ineff= 2 , 0
       0                               0
Bank Sta=9900.173,10123.12
Exp/Cntr=0.3,0.1

Type RM Length L Ch R = 1 , 14543.5,248.141300,248.141300,248.141300
XS GIS Cut Line= 6
574380.220883786804289.658656455574358.467208534804323.194966659
574289.718806177804415.668508217574274.039306253804444.595330477
574264.736612558804471.767087355574260.652815163804504.293035537
#Sta/Elev= 30
9886.907873.9925 9890.67872.02719893.139870.95179905.109 861.693 9917.08858.5387
 9926.89853.8051 9929.15852.62659941.673 843.7959949.261840.13489954.196 838.877
9979.243836.82039986.212836.79169991.854836.48249998.812835.424410004.52835.2355
10015.25837.084610017.03837.844610029.18849.326110032.85854.386210041.33862.4686
10052.76865.594410064.13868.059510073.03868.256610075.05867.979910086.05866.8431
10096.61864.926610102.95864.200610117.16863.841710128.03863.9865 10136.6864.3053
#Mann= 3 , 0 , 0
9886.907    0.12       09886.907    0.12       0 10136.6    0.12       0
#XS Ineff= 2 , 0
       0                               0
Bank Sta=9886.907,10136.6
Exp/Cntr=0.3,0.1

Type RM Length L Ch R = 1 ,14295.36,247.998400,247.998400,247.998400
XS GIS Cut Line= 6
573865.549209803804245.948259234574125.401965737804373.194412604
574165.557089001804395.935416996574186.068312526804411.584748775
574203.417886794804432.885518163 574237.46748656804512.335018039
#Sta/Elev= 30
9699.005884.93089720.662873.30239742.931869.19139754.066874.38659776.335876.9666
 9787.47884.69579798.604885.56089820.874 882.4269832.008882.80189843.143889.9979
9854.277892.77079876.547895.92939887.681893.46439898.816892.3947 9909.95  896.16
9921.085890.76349946.969861.59179954.489854.91789965.623842.88669976.758833.5975
9987.892829.7866    9999829.261610012.52831.892610022.32836.157710033.85844.0064
10064.69852.765310112.74 855.03910145.06858.044410166.48862.948810174.33862.8758
#Mann= 3 , 0 , 0
9699.005    0.12       09699.005    0.12       010174.33    0.12       0
#XS Ineff= 2 , 0
       0                               0
Bank Sta=9699.005,10174.33
Exp/Cntr=0.3,0.1

Type RM Length L Ch R = 1 ,14047.36,247.998500,247.998500,247.998500
XS GIS Cut Line= 6
573786.035958886804551.099132657573853.057812274804575.409258038
573914.899021327804592.432514042574127.544870019804627.372961193
574164.435933083804635.720958427574209.986840069804653.354125276
#Sta/Elev= 30
9699.051930.32289708.586924.78519729.861915.35389751.136907.88139761.774902.8183
9793.104890.24699813.847883.65419824.219877.65239844.778875.25699854.967868.3183
9865.156 863.6869885.534862.12569915.966862.30619926.068858.35859936.169852.7366
 9946.27845.88779966.472829.30099976.573827.01449986.674826.6977 10006.9828.1543
10017.04828.128110037.32837.311810047.46840.865910057.68841.781110078.19845.2232
10088.45847.8632 10109.5850.2373 10120.2855.662310131.28860.1423 10136.8860.6608
#Mann= 3 , 0 , 0
9699.051    0.12       09699.051    0.12       0 10136.8    0.12       0
#XS Ineff= 2 , 0
       0                               0
Bank Sta=9699.051,10136.8
Exp/Cntr=0.3,0.1

Type RM Length L Ch R = 1 ,13799.37,247.998400,247.998400,247.998400
XS GIS Cut Line= 6
573790.464357911 804760.11643364573868.499819562804814.509926099
 573938.68210782804847.338613923574202.073696585804884.511597962
 574277.72232187804910.085712656574350.680879989804948.915148354
#Sta/Elev= 30
9699.076 895.6759707.363893.90139741.823 881.242  9754.2878.29699766.149876.4245
9778.097875.72199801.637872.17599813.034869.55169846.292855.3095 9857.08847.7913
9867.867841.51289888.794837.76079909.259837.26189929.589833.59969939.635833.1521
9979.821824.79999999.913   824.310019.99824.415510030.03828.154310080.32836.1217
10090.48839.771710110.79850.243210120.95 854.37610162.19868.144710204.55885.2882
10237.43884.908710260.16882.694910273.22887.194410282.78895.170910300.92906.9282
#Mann= 3 , 0 , 0
9699.076    0.12       09699.076    0.12       010300.92    0.12       0
#XS Ineff= 2 , 0
       0                               0
Bank Sta=9699.076,10300.92
Exp/Cntr=0.3,0.1

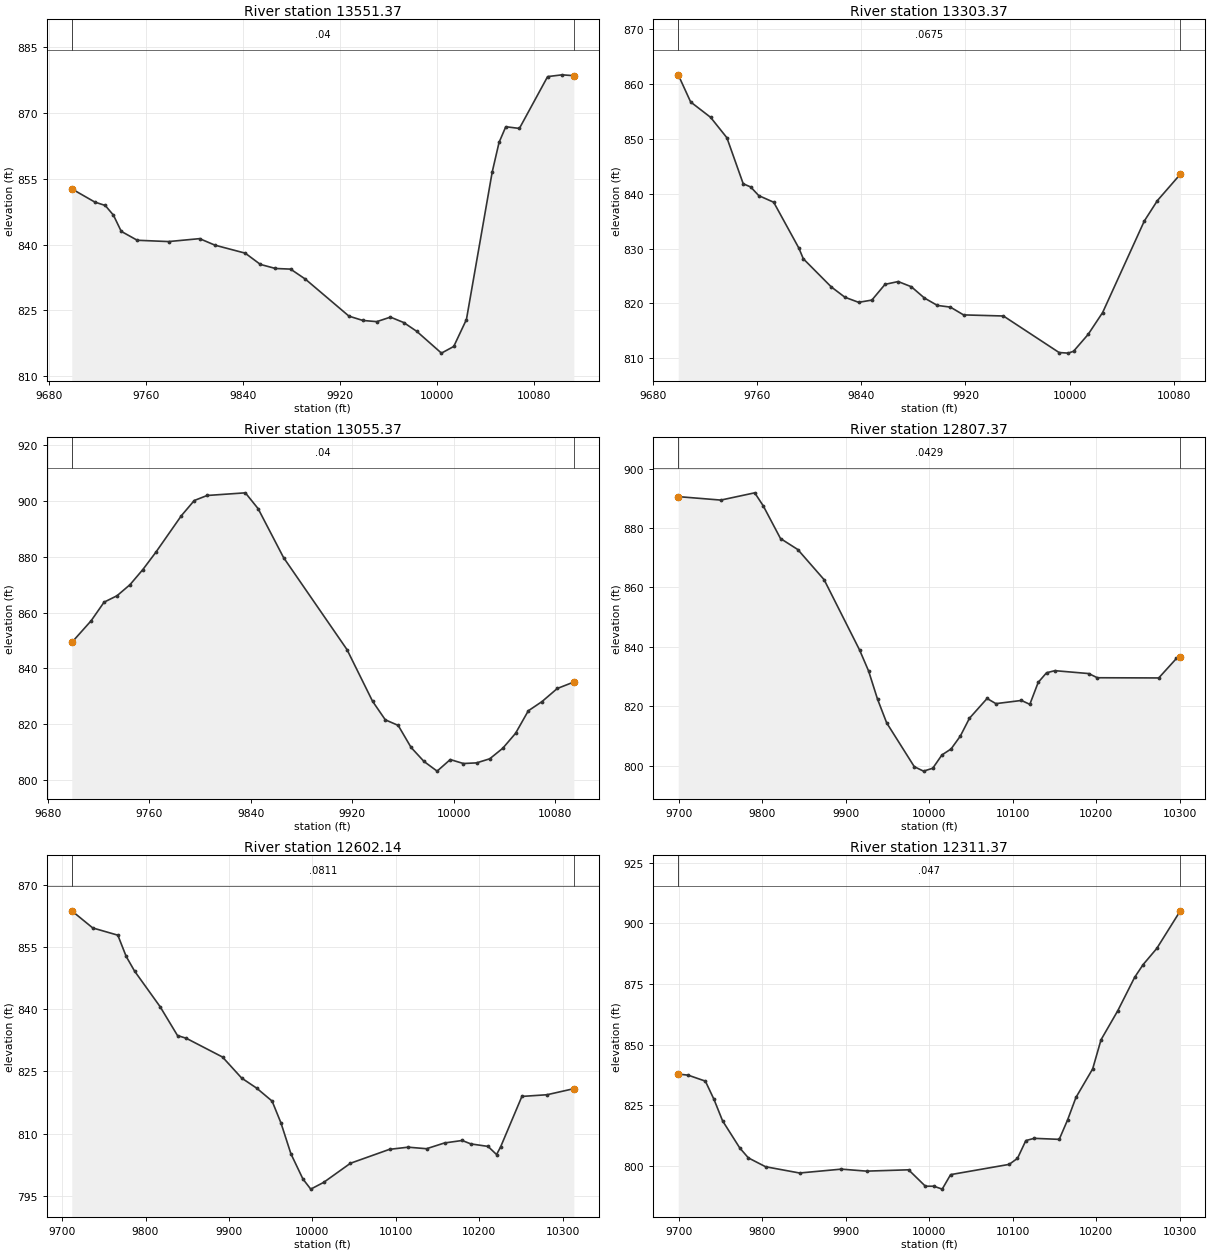
Type RM Length L Ch R = 1 ,13551.37,247.998500,247.998500,247.998500
XS GIS Cut Line= 6
573832.556712812804844.100981302573905.783531246804932.087114261
573971.797957368805024.603905612573995.768529214805071.665518366
574012.219974199805134.562765155574046.292039031 805193.09522127
#Sta/Elev= 30
9699.095  852.669718.147849.64929726.693848.88249733.459846.67749739.898 842.992
9753.104840.96389778.927 840.6669804.519841.33319817.219839.8467 9842.16838.0293
9854.631835.47119867.101 834.5429879.572834.39889891.725832.12479927.733823.6938
9939.182822.71529950.631822.44629961.922823.47529972.858822.24179983.561820.2522
10003.98 815.28110014.14   816.810024.59822.929910045.84856.484810051.49863.2215
10057.05866.802310068.27866.413610091.55878.2052 10103.5878.610610113.18878.4135
#Mann= 3 , 0 , 0
9699.095    0.04       09699.095    0.04       010113.18    0.04       0
#XS Ineff= 2 , 0
       0                               0
Bank Sta=9699.095,10113.18
Exp/Cntr=0.3,0.1

Type RM Length L Ch R = 1 ,13303.37,247.998400,247.998400,247.998400
XS GIS Cut Line= 6
573709.229734004804785.206770152573761.009223223804861.867423341
573782.917072177804944.009022579573777.666406572805006.593423635
573734.595172763805112.444063932573731.951141566805142.383787066
#Sta/Elev= 30
9699.227861.69559708.775 856.7439724.071853.94939736.622850.22129749.174841.8261
9754.907841.24119761.137839.66169772.604838.45559791.947830.08889795.366828.1444
9816.882 823.0089827.386  821.12 9837.89820.2003 9848.07820.60679858.186823.4783
9868.303823.98749878.408823.04189888.408820.99379898.408819.6334 9908.43819.3243
9918.543817.90659949.197817.70549991.971811.0424    9999810.932510003.09811.2735
10014.28814.339910025.46818.342410057.49835.032610067.59838.770510085.16843.5576
#Mann= 3 , 0 , 0
9699.227  0.0675       09699.227  0.0675       010085.16  0.0675       0
#XS Ineff= 2 , 0
       0                               0
Bank Sta=9699.227,10085.16
Exp/Cntr=0.3,0.1

Type RM Length L Ch R = 1 ,13055.37,247.998500,247.998500,247.998500
XS GIS Cut Line= 6
573310.078163713805112.074095204573411.939478785805130.316637188
573495.059313804805136.127199829573556.611801118805132.429613382
573656.420434296 805110.52600272573694.693210542805130.767109513
#Sta/Elev= 30
9699.049849.33059714.283857.09339724.493863.76869734.703 866.0779744.913870.0391
9755.066875.47939765.185881.61669785.422894.80729795.541900.22089805.638902.0218
9835.787 902.9779845.829897.30369865.846879.77979915.871846.74269935.959828.2511
9946.005821.58739956.159819.58249966.334811.66769976.509806.64719986.823 803.186
9997.174807.335610007.54805.912810017.91806.146210028.28807.611310038.52811.3882
10048.57816.719810058.65824.8207 10069.4828.110710081.46832.817110094.52835.1393
#Mann= 3 , 0 , 0
9699.049    0.04       09699.049    0.04       010094.52    0.04       0
#XS Ineff= 2 , 0
       0                               0
Bank Sta=9699.049,10094.52
Exp/Cntr=0.3,0.1

Type RM Length L Ch R = 1 ,12807.37,205.231300,205.231300,205.231300
XS GIS Cut Line= 6
573404.338738578805438.426541925573549.915079862805411.037116747
  573736.7121458805333.369677408573790.613469476805318.239713106
573871.164765783805321.097244462573979.427053005805355.871060794
#Sta/Elev= 30
 9699.07890.60739750.114889.44089790.754 891.8879800.971887.49529821.665876.4881
9842.389 872.7799873.911862.62869916.499838.89879927.225 831.8739937.952822.3753
9948.905814.38589982.032799.61289993.074798.125210004.14799.097710015.14803.5758
10026.13805.604810037.13809.899810048.13815.935810069.28822.603210079.82820.8638
10110.47821.9382 10120.5820.623510130.53828.020710140.56831.267310150.59831.9697
10191.09830.997210201.45829.586610275.02829.519710296.19836.074410300.88836.6201
#Mann= 3 , 0 , 0
 9699.07  0.0429       0 9699.07  0.0429       010300.88  0.0429       0
#XS Ineff= 2 , 0
       0                               0
Bank Sta=9699.07,10300.88
Exp/Cntr=0.3,0.1

Type RM Length L Ch R = 1 ,12602.14,290.765600,290.765600,290.765600
XS GIS Cut Line= 6
573509.865662619805630.176961642573584.381962036 805627.60103782
573653.304795939805609.443908673573923.313888187805459.160862829
573992.185760519805442.582905336574067.167488079805439.192967275
#Sta/Elev= 30
9711.567 863.7289736.712859.59879766.784857.85099776.809 852.7229786.846849.1925
9817.487840.59289838.317833.63829848.856832.97899892.283828.4546 9915.22823.3762
9933.246820.94429951.716817.81949962.353812.53789974.247805.11519988.656799.0284
9998.035796.585510013.48798.208110045.63802.827610092.45806.183910114.71806.7057
10136.83806.334210158.39807.725510179.55808.319910189.98807.493810210.59806.8909
10220.77804.922610225.58806.754610251.14818.951910281.24819.357710313.41820.8234
#Mann= 3 , 0 , 0
9711.567  0.0811       09711.567  0.0811       010313.41  0.0811       0
#XS Ineff= 2 , 0
       0                               0
Bank Sta=9711.567,10313.41
Exp/Cntr=0.3,0.1

Type RM Length L Ch R = 1 ,12311.37,247.998400,247.998400,247.998400
XS GIS Cut Line= 6
573633.458165011805758.487028518573743.792842394805786.243380484
573802.235288664805794.003365712574054.698824478805771.734447912
574136.802881913805775.570992696574228.882070893 805790.00279112
#Sta/Elev= 30
9699.057837.81329710.958837.35089731.581834.88939741.893827.36699752.204818.5084
9772.827807.29049783.139803.19229803.762799.53969844.507796.95349894.626798.5487
9924.751797.72429975.191798.27079995.367791.491810005.45 791.49910015.51790.2935
10025.57796.280910095.75  800.5110105.76803.002810115.78810.349610125.79811.2656
10155.79810.845410165.81818.865510175.83828.154110195.88839.9416 10205.9851.9702
10226.05864.0031 10246.2877.751410256.36883.011810272.72889.671310300.95905.2114
#Mann= 3 , 0 , 0
9699.057   0.047       09699.057   0.047       010300.95   0.047       0
#XS Ineff= 2 , 0
       0                               0
Bank Sta=9699.057,10300.95
Exp/Cntr=0.3,0.1

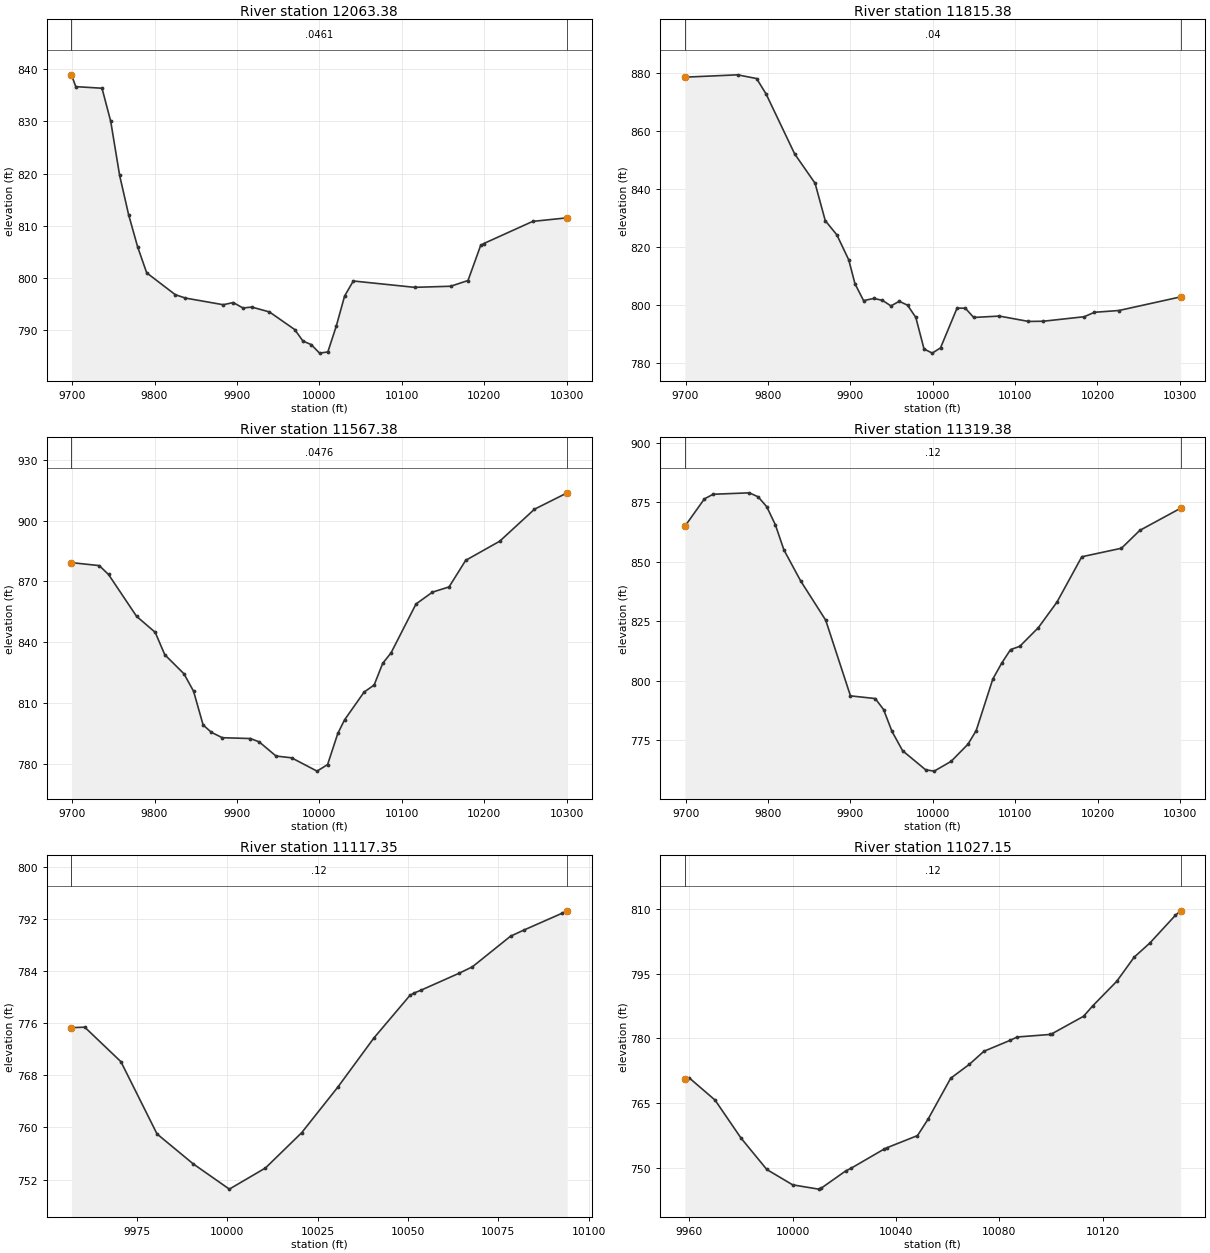
Type RM Length L Ch R = 1 ,12063.38,247.998500,247.998500,247.998500
XS GIS Cut Line= 6
573630.026978247805764.283488322573718.514039358805799.031356377
573780.075521199805845.577243501573809.884899206805899.366675721
573845.461205671 806043.30615202574003.910629018806190.897631104
#Sta/Elev= 30
9699.196838.92959704.468836.66529736.268836.36069746.868829.99769757.666819.6466
9768.608812.0903 9779.55805.93499790.491800.97419825.268 796.778 9837.54796.1356
9883.411794.85849895.583795.27649907.299794.23499918.161794.40779939.539 793.471
9970.132790.10259980.185787.89459990.238787.211210000.29785.579910010.36785.8089
10020.53790.7239 10030.7796.520310041.24799.409710115.58798.1925 10159.4   798.4
10180.48799.499710195.81806.219510199.61806.588510259.01810.833710300.86811.5183
#Mann= 3 , 0 , 0
9699.196  0.0461       09699.196  0.0461       010300.86  0.0461       0
#XS Ineff= 2 , 0
       0                               0
Bank Sta=9699.196,10300.86
Exp/Cntr=0.3,0.1

Type RM Length L Ch R = 1 ,11815.38,247.998400,247.998400,247.998400
XS GIS Cut Line= 6
573470.946975688805909.326189367573535.578678542806022.917510576
573583.144692207806078.770838232573620.779094783806095.760060358
573771.926483213806117.060290237573938.186577595806231.007670597
#Sta/Elev= 30
9699.212878.41589763.267879.22349786.278877.93999797.783872.6231 9832.48851.9764
9857.228841.87319869.602828.98569883.652824.0969  9898.1815.47999905.684807.2239
9916.104801.43829928.584802.18559939.044801.52299949.344799.60319959.426801.2118
9969.501799.83989979.501795.64929989.502784.75779999.503 783.343 10009.5785.1687
10029.54 798.84610039.58798.825110049.77795.632410080.86796.110210116.26794.2613
10134.01794.326410183.94795.884710196.28797.412810226.02798.026710300.91802.7258
#Mann= 3 , 0 , 0
9699.212    0.04       09699.212    0.04       010300.91    0.04       0
#XS Ineff= 2 , 0
       0                               0
Bank Sta=9699.212,10300.91
Exp/Cntr=0.3,0.1

Type RM Length L Ch R = 1 ,11567.38,247.998500,247.998500,247.998500
XS GIS Cut Line= 6
573492.533023741805955.243852913573603.358127897806161.586311065
573548.385628404806253.618368422573533.316031514806315.684638492
573541.929132738806406.577490023573575.716972158 806501.81143992
#Sta/Elev= 30
9699.203879.22919732.894  877.779744.216 873.3839778.184852.77159800.829844.8614
9812.451833.82589835.717824.4171 9847.35815.84629858.983799.17449868.981795.5546
9882.249792.89169916.456792.47669927.055790.82099947.441783.85199966.357782.9716
 9997.19776.4093   10010779.631310022.43795.013910030.59801.687710054.31815.3982
 10066.5818.877910076.88829.559610087.01834.7332 10117.3858.8331 10137.3864.6895
10157.37867.237510177.59880.360910218.86889.791510261.07905.581110300.77 913.653
#Mann= 3 , 0 , 0
9699.203  0.0476       09699.203  0.0476       010300.77  0.0476       0
#XS Ineff= 2 , 0
       0                               0
Bank Sta=9699.203,10300.77
Exp/Cntr=0.3,0.1

Type RM Length L Ch R = 1 ,11319.38,202.033300,202.033300,202.033300
XS GIS Cut Line= 6
573303.308343469805845.231312672573341.590880191805922.839540669
573359.064612873805999.781123801573358.751553771806062.057447782
573337.135955291806204.771069331 573435.29826444806410.539859411
#Sta/Elev= 30
9699.127864.98789722.801876.49979733.362878.44489777.292879.04869788.062 877.376
9798.494873.21719808.927865.64549819.359855.0518 9839.72842.00089870.077825.5346
9900.111793.74749930.196792.6186 9940.33787.99249950.464778.86039963.399770.6998
9991.471762.653310001.78762.125310022.31766.246910042.72773.420310052.74779.1648
10072.96800.862510083.69807.501710094.42813.181510105.61814.5515 10128.2 822.416
10150.79833.142710180.92852.192910229.02855.761910251.34863.276310300.87872.5867
#Mann= 3 , 0 , 0
9699.127    0.12       09699.127    0.12       010300.87    0.12       0
#XS Ineff= 2 , 0
       0                               0
Bank Sta=9699.127,10300.87
Exp/Cntr=0.3,0.1

Type RM Length L Ch R = 1 ,11117.35,90.201100,90.201100,90.201100
XS GIS Cut Line= 3
573201.320401132806223.619104937573296.174396485806223.619104937
573326.094784319806253.539492726
#Sta/Elev= 19
9956.886775.34189960.565775.41669970.565770.11829980.565759.00579990.565 754.412
10000.57750.525810010.57753.777610020.57  759.1910030.57 766.19510040.57773.7601
10050.57 780.32410051.74780.676410053.69781.123510064.22783.726410067.83784.6985
10078.36789.395310081.98790.322910092.51792.895710094.05793.2987
#Mann= 3 , 0 , 0
9956.886    0.12       09956.886    0.12       010094.05    0.12       0
#XS Ineff= 2 , 0
       0                               0
Bank Sta=9956.886,10094.05
Exp/Cntr=0.3,0.1

Type RM Length L Ch R = 1 ,11027.15,29.716900,29.716900,29.716900
XS GIS Cut Line= 3
573227.332243979806263.338605076573229.087448925806315.994753033
573316.262627214806424.232390508
#Sta/Elev= 28
9958.382770.65629960.045770.8767 9970.05765.71229980.056 756.9269990.061749.6111
10000.07746.047610010.07 745.05710011.07745.265410020.49749.246510022.63749.8934
10035.47754.371910036.44 754.64410048.31757.474210052.38761.252710061.15770.7814
10068.32773.982810073.99777.034510084.26779.606410086.83780.347310099.67780.9406
10100.21781.070210112.51785.149610116.15787.620110125.35793.265210132.09798.8694
10138.19802.167110148.03808.581110150.05809.6156
#Mann= 3 , 0 , 0
9958.382    0.12       09958.382    0.12       010150.05    0.12       0
#XS Ineff= 2 , 0
       0                               0
Bank Sta=9958.382,10150.05
Exp/Cntr=0.3,0.1