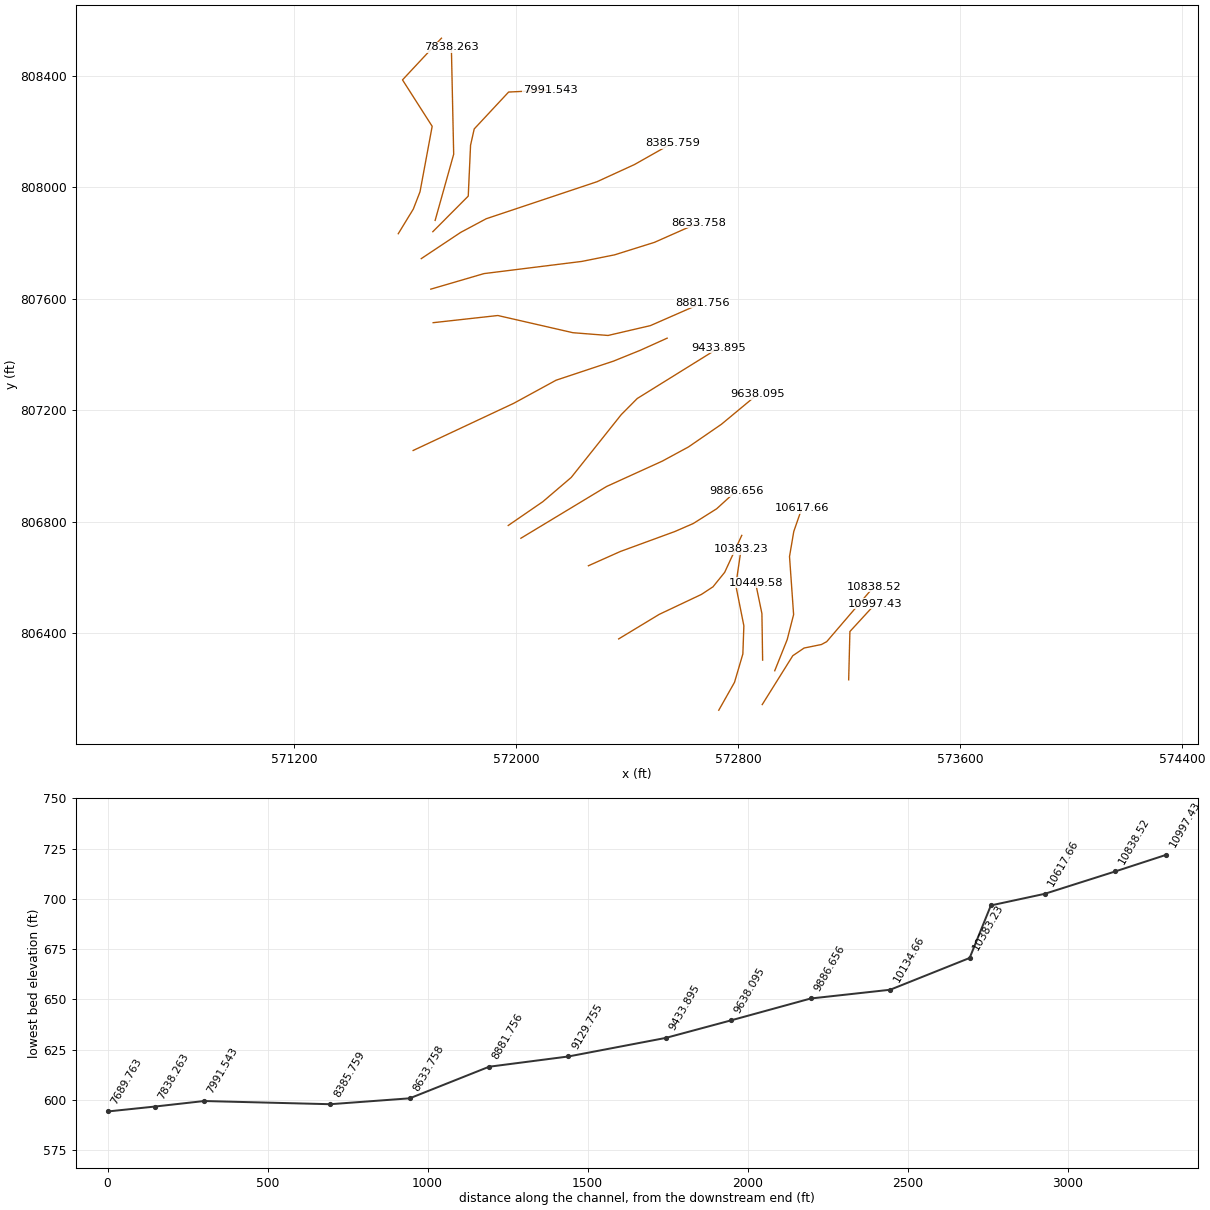
HEC-RAS study 11111_ras.prj: 11111

--- 11111_ras.g01 (geometry) --- (continued)

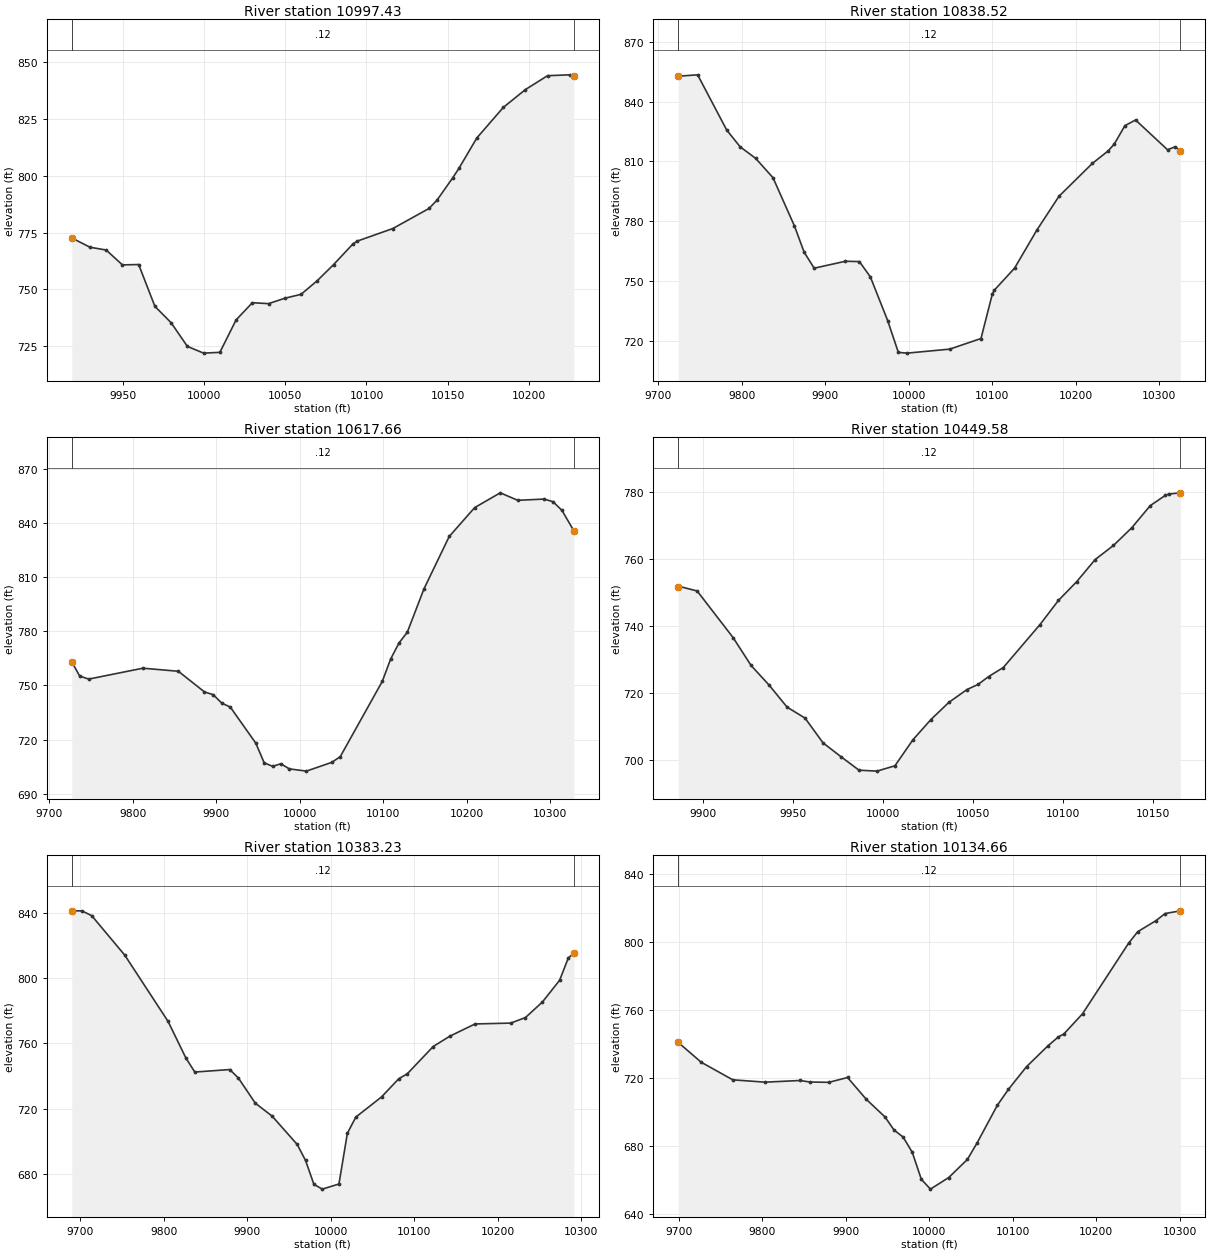
Type RM Length L Ch R = 1 ,10997.43,158.913800,158.913800,158.913800
XS GIS Cut Line= 3
573198.773985147806233.804768845573203.230213135806406.961055666
573295.537792504806506.907883003
#Sta/Elev= 30
 9918.47772.61629929.669768.52839939.672767.28899949.676760.75519959.679 760.911
9969.682742.50129979.686 735.2959989.689724.88249999.692721.9223 10009.7722.2718
 10019.7736.5409 10029.7744.105110039.71743.703710049.71746.080410059.71747.7976
10069.72753.821410079.72760.865810091.68769.988510094.29771.207710116.24776.7567
10138.51785.574710143.46 789.25910153.25799.179210157.08803.384810167.99816.6236
 10184.3830.059110197.91837.906910211.53844.004110225.14 844.39310227.74843.9743
#Mann= 3 , 0 , 0
 9918.47    0.12       0 9918.47    0.12       010227.74    0.12       0
#XS Ineff= 2 , 0
       0                               0
Bank Sta=9918.47,10227.74
Exp/Cntr=0.3,0.1

Type RM Length L Ch R = 1 ,10838.52,220.852100,220.852100,220.852100
XS GIS Cut Line= 6
572887.352088927806144.978925723572997.355507249806320.074280631
573038.091327772806347.671425884573100.705138824806360.371997332
573119.609423406806370.559415092573288.808558292806567.001060613
#Sta/Elev= 30
9723.674852.75249746.911853.45159781.729825.7377 9797.85817.30769816.547811.4664
9837.255801.7596 9862.97777.50339874.576 764.3569886.588756.33439924.045 759.815
9940.811759.65559953.914751.97259974.681729.98939987.462714.04789997.912713.6722
10049.02715.6818 10086.5721.017510100.08743.338210102.47745.284410126.74756.3522
 10153.4 775.43610180.05792.497910220.04808.985210238.82815.214410246.21 818.674
10258.97827.915910271.74830.771210310.04815.825410319.24817.303610325.37815.2945
#Mann= 3 , 0 , 0
9723.674    0.12       09723.674    0.12       010325.37    0.12       0
#XS Ineff= 2 , 0
       0                               0
Bank Sta=9723.674,10325.37
Exp/Cntr=0.3,0.1

Type RM Length L Ch R = 1 ,10617.66,168.080300,168.080300,168.080300
XS GIS Cut Line= 6
572932.398370773806266.239023765572977.209755949806377.719416019
573000.390750198806467.608318365572985.648914261806675.931470189
573000.992177135806765.655507649573029.751376998806848.274371155
#Sta/Elev= 30
9726.708763.11289736.229755.15059747.097753.50179811.914759.53129854.481 757.834
9885.787746.37889896.223744.87379906.504740.18279916.714738.01379947.257718.0354
9957.347707.13569967.384705.15639977.387706.58759987.461703.764410007.89702.5054
10038.42707.367810048.54710.518510098.92752.236810108.94 764.60510118.94773.4946
10128.95779.517910148.95 803.55210179.14832.506710209.67848.509610240.35 856.703
10261.26852.563410292.87853.241210303.59851.790610314.32846.975810328.55 835.662
#Mann= 3 , 0 , 0
9726.708    0.12       09726.708    0.12       010328.55    0.12       0
#XS Ineff= 2 , 0
       0                               0
Bank Sta=9726.708,10328.55
Exp/Cntr=0.3,0.1

Type RM Length L Ch R = 1 ,10449.58,66.352000,66.352000,66.352000
XS GIS Cut Line= 3
572888.747839272806304.467812374572886.201423287806471.258059248
572863.283679456806581.390550494
#Sta/Elev= 30
9886.115751.78239886.647751.81989896.648750.44159916.651736.53629926.652728.2351
9936.653722.39839946.654715.82559956.655712.55619966.657705.17489976.658701.0372
9986.659697.0261 9996.66696.739710006.66698.334110016.66706.078410026.66712.1039
10036.66717.237910046.67721.038610052.92722.591810058.82724.944610066.96727.6306
10087.39740.4518 10097.6747.617810107.82753.246510118.03759.809210128.25764.0276
10138.46769.323310148.67775.878810156.99778.912810158.89779.333310165.42779.7095
#Mann= 3 , 0 , 0
9886.115    0.12       09886.115    0.12       010165.42    0.12       0
#XS Ineff= 2 , 0
       0                               0
Bank Sta=9886.115,10165.42
Exp/Cntr=0.3,0.1

Type RM Length L Ch R = 1 ,10383.23,248.573100,248.573100,248.573100
XS GIS Cut Line= 6
572730.718316474806124.705212027572787.494244862806224.794979731
 572817.54875008806326.488763475572821.163349916806427.463764738
572792.010604615 806572.69979146572811.036532555806701.432013389
#Sta/Elev= 30
9689.594841.40499701.712841.37199713.484838.44779753.137814.18829804.996 773.554
9826.354751.10849837.032742.45699879.014743.9966 9889.31738.77339909.614723.3363
9929.699 715.4339959.791698.02859969.793688.20759979.796673.56859989.799 670.603
10009.82673.743910019.93704.883410030.08714.827710060.88727.191710081.54 738.361
10091.87 741.44810122.75758.124810142.88764.5158   10173 771.98310215.69772.5005
10233.39775.906410253.72785.457510274.36798.824510284.71 812.48310291.37815.3227
#Mann= 3 , 0 , 0
9689.594    0.12       09689.594    0.12       010291.37    0.12       0
#XS Ineff= 2 , 0
       0                               0
Bank Sta=9689.594,10291.37
Exp/Cntr=0.3,0.1

Type RM Length L Ch R = 1 ,10134.66,248.001900,248.001900,248.001900
XS GIS Cut Line= 6
572370.068867871806380.401538074572515.959578408806468.307787459
572668.303989443806540.026500066572710.035432684806567.400225131
572752.060844971806619.218898772572813.560037577806751.676312604
#Sta/Elev= 30
9699.027 740.9449726.632729.27859764.451718.97329803.062717.60869845.136718.5812
9856.701717.70529879.534717.50449902.008720.34369924.482707.50759946.837697.2052
9957.737689.45919968.636685.35389979.536676.43419990.436660.552810001.32654.7795
10023.25661.582910045.58672.185810057.15681.803110081.51704.0077 10094.9713.4226
10116.56726.729110142.43739.042410154.79744.224910161.26745.903610183.66757.7727
10238.86799.1983 10249.8805.980110271.68812.456310282.62816.637710300.87818.2366
#Mann= 3 , 0 , 0
9699.027    0.12       09699.027    0.12       010300.87    0.12       0
#XS Ineff= 2 , 0
       0                               0
Bank Sta=9699.027,10300.87
Exp/Cntr=0.3,0.1

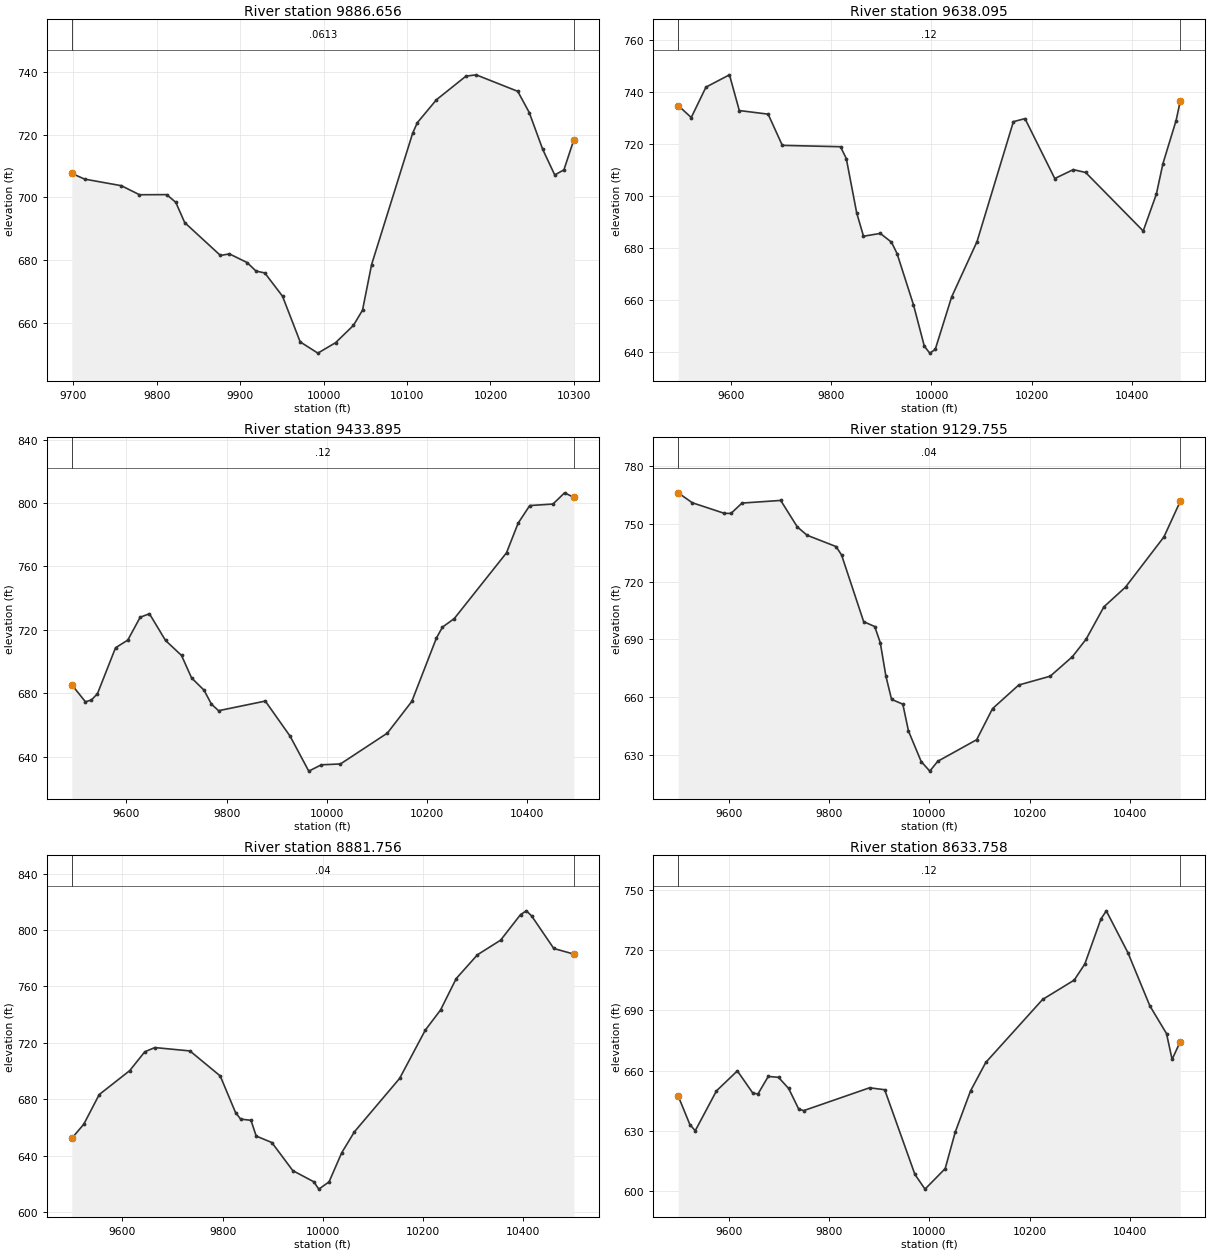
Type RM Length L Ch R = 1 ,9886.656,248.561200,248.561200,248.561200
XS GIS Cut Line= 6
572261.097061677806642.808766537572375.662754784806693.773116336
572573.000140933806765.759487076572638.699081106806794.206487139
572723.057658818806847.090453389572793.563306398 806910.89197398
#Sta/Elev= 30
9698.089707.62479713.438705.81389757.512703.71169779.266700.83439811.898700.8686
9822.775 698.4229833.497 691.9649876.339681.50499887.049682.01579908.336679.2487
9918.935676.56179929.534 675.9439950.732668.54559971.929654.00789993.127650.4352
 10014.4 653.76810035.75659.257110046.65664.109210057.54 678.62310106.79720.4434
10112.38723.761210135.28  731.0610170.65738.568810182.84738.987810232.75733.7379
10246.51726.9974 10262.7715.2548 10277.1707.1257 10288.1708.7595   10300718.3275
#Mann= 3 , 0 , 0
9698.089  0.0613       09698.089  0.0613       0   10300  0.0613       0
#XS Ineff= 2 , 0
       0                               0
Bank Sta=9698.089,10300
Exp/Cntr=0.3,0.1

Type RM Length L Ch R = 1 ,9638.095,204.199900,204.199900,204.199900
XS GIS Cut Line= 6
572017.795291651806741.463925058572326.382573458806926.977662855
572527.448797081807018.105985416572621.778567685807068.989089858
572740.227557515807150.144411708572871.415831786807258.471085894
#Sta/Elev= 30
9494.605734.80989520.569730.19749549.923741.89259596.797746.62529616.473732.8847
9674.016731.49959702.265719.49469818.461718.97099830.004714.39539850.727693.5209
9864.308684.53559897.805685.62739920.137682.25679931.303677.86069963.974658.2123
9985.682642.25759996.525639.570810007.43 640.97610040.14661.157510090.83682.4725
10163.43728.604910186.56729.785510245.99706.739610282.96 710.159 10307.6 709.065
10422.49686.551910448.73700.728610461.86712.483110488.11729.037610496.53736.6397
#Mann= 3 , 0 , 0
9494.605    0.12       09494.605    0.12       010496.53    0.12       0
#XS Ineff= 2 , 0
       0                               0
Bank Sta=9494.605,10496.53
Exp/Cntr=0.3,0.1

Type RM Length L Ch R = 1 ,9433.895,304.140600,304.140600,304.140600
XS GIS Cut Line= 6
571972.215863182806787.257752858572097.085327801806872.745541126
572199.132414702806959.506197339572379.062487418807184.431054071
572436.918777073807242.535848077572730.975331916807424.369699039
#Sta/Elev= 30
9490.968685.33429518.293674.54049530.286675.73149542.278679.70469578.257708.6311
9602.758713.49189627.423727.86819645.935730.11639678.078713.24629709.957703.8185
9730.077689.61369754.855681.90479769.668673.07369783.946668.94869877.166675.0151
9926.609652.89689963.895630.82599988.925634.815310027.17635.353110120.76654.8162
 10169.5674.797110218.76714.877810230.74721.681910254.22727.046810358.49768.5493
10381.66787.227110404.83798.343210451.17799.294310474.34806.375910492.85803.4977
#Mann= 3 , 0 , 0
9490.968    0.12       09490.968    0.12       010492.85    0.12       0
#XS Ineff= 2 , 0
       0                               0
Bank Sta=9490.968,10492.85
Exp/Cntr=0.3,0.1

Type RM Length L Ch R = 1 ,9129.755,247.998400,247.998400,247.998400
XS GIS Cut Line= 6
571629.707341853 807056.22135628571991.968771595807225.351079045
572144.606118264807308.227555558572351.523895998807376.702370822
572447.398247591807415.314112832572544.819819158807459.024309905
#Sta/Elev= 30
9499.037766.19449526.951761.05129590.704755.56569604.204755.47549626.276760.8735
9703.529762.24469736.638 748.4969756.174744.15459813.891 738.2889824.927733.9324
9869.072699.24559891.144696.72339902.243688.28129913.487 670.888 9924.73658.8856
9947.218656.38779958.461642.45499983.887 626.561   10001621.596810016.86   626.7
10094.56637.923510126.18654.065710178.45666.329110241.42 670.93410285.71681.0842
10313.01690.180710348.45706.958210391.57717.200810468.25 743.28910500.93761.8416
#Mann= 3 , 0 , 0
9499.037    0.04       09499.037    0.04       010500.93    0.04       0
#XS Ineff= 2 , 0
       0                               0
Bank Sta=9499.037,10500.93
Exp/Cntr=0.3,0.1

Type RM Length L Ch R = 1 ,8881.756,247.998500,247.998500,247.998500
XS GIS Cut Line= 6
571701.712317134 807514.54658256571934.772285906807540.238768406
572205.250997838807478.595219029572331.769639915807468.688644227
572484.247115752807503.937014438572671.151290088807585.386864549
#Sta/Elev= 30
9499.105652.43249523.034662.4428 9553.86683.4532 9614.62700.38289644.794713.7598
9664.821716.73929734.871714.35649795.283696.6606 9825.86670.74729836.052 666.073
9856.715665.22159867.067654.07699898.275649.49559940.182629.57449981.813621.7394
9992.076616.483610012.48621.632310037.78642.278110063.01657.049610153.31694.9186
10204.52729.113110234.93743.361710266.21765.620110308.45 782.43610354.81792.8108
10394.57810.937110406.33813.580910416.69809.949910460.92786.9036 10500.9 782.935
#Mann= 3 , 0 , 0
9499.105    0.04       09499.105    0.04       0 10500.9    0.04       0
#XS Ineff= 2 , 0
       0                               0
Bank Sta=9499.105,10500.9
Exp/Cntr=0.3,0.1

Type RM Length L Ch R = 1 ,8633.758,247.998500,247.998500,247.998500
XS GIS Cut Line= 6
571693.203724473807634.774955919571884.995828824807690.594281702
572237.569350986807734.287310061572355.358922802807757.807408587
572499.209536401807802.682387256572659.802174322807873.505527664
#Sta/Elev= 30
9499.032647.23229522.282633.02069532.949 629.9279575.337649.85659617.025659.8386
9647.945648.70959658.179648.32019678.645657.05579699.112656.61699719.395651.0347
9739.679640.64539749.821  640.029880.839651.38349911.012650.41349971.356608.1162
9991.471600.772110031.73611.022510051.87 629.30910082.29649.806510112.74664.0498
10226.19695.5145 10289.2705.167110310.34 713.17310342.43 735.65710353.25739.7662
 10396.5718.801810440.17692.311210473.44678.444910484.53 665.58610500.94674.4741
#Mann= 3 , 0 , 0
9499.032    0.12       09499.032    0.12       010500.94    0.12       0
#XS Ineff= 2 , 0
       0                               0
Bank Sta=9499.032,10500.94
Exp/Cntr=0.3,0.1

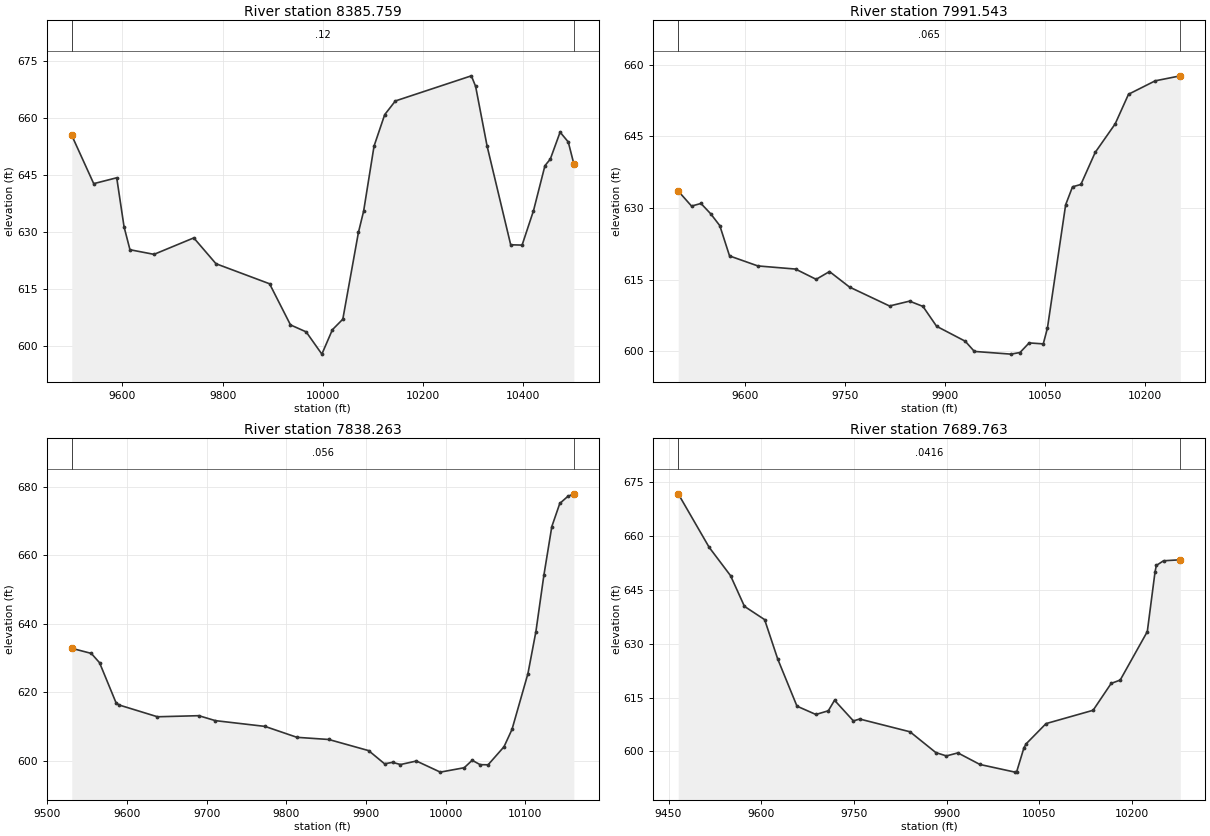
Type RM Length L Ch R = 1 ,8385.759,394.216200,394.216200,394.216200
XS GIS Cut Line= 6
571658.875559294807744.286847863571800.665062516807838.188120289
571892.938335462807887.301517141572292.265481125 808020.14472909
 572427.04970591808081.656006512 572564.56166326808159.011753494
#Sta/Elev= 30
9499.054 655.4419542.849642.73139588.756644.28019603.374631.3782 9615.19625.3325
9663.164624.1147 9742.52628.44859786.832621.64569893.752616.36719935.503605.5368
9966.816603.6979 9998.13597.840610019.15604.270710039.92 607.03810071.08629.8886
10081.47635.495910102.27652.629310123.51660.899710144.75664.507310296.42671.1258
10304.93668.351710327.87652.603310374.93626.635710397.68626.550610420.43635.6094
10443.29647.470210453.94649.187610473.52656.293710489.82653.707310500.95647.9381
#Mann= 3 , 0 , 0
9499.054    0.12       09499.054    0.12       010500.95    0.12       0
#XS Ineff= 2 , 0
       0                               0
Bank Sta=9499.054,10500.95
Exp/Cntr=0.3,0.1

Type RM Length L Ch R = 1 ,7991.543,153.280200,153.280200,153.280200
XS GIS Cut Line= 6
571700.542983323807840.880109683571828.126786977807968.463913321
571836.473390967  808150.8968288571849.589482903808209.323056638
571973.596170574808341.676348269572122.642670184808348.830580235
#Sta/Elev= 30
9499.958633.55489519.926630.41099534.069630.95919548.687628.79649562.353626.3103
9576.972619.97779619.398617.88459675.967 617.2299706.952 615.0799726.973616.7067
9757.005613.46379817.068609.50059847.099 610.5149867.218609.41489887.715605.2535
9930.672602.12819944.376599.99119999.189599.424410012.89599.7639 10026.6601.7718
10047.81601.5691   10054604.835810081.41630.686110091.69634.443210104.26634.9329
10125.69641.629110155.73647.616510175.75653.816510215.79656.622710253.48657.6712
#Mann= 3 , 0 , 0
9499.958   0.065       09499.958   0.065       010253.48   0.065       0
#XS Ineff= 2 , 0
       0                               0
Bank Sta=9499.958,10253.48
Exp/Cntr=0.3,0.1

Type RM Length L Ch R = 1 ,7838.263,148.499700,148.499700,148.499700
XS GIS Cut Line= 3
571708.889587313807881.420757562571775.662419111808118.702784881
571767.315815151808502.646567822
#Sta/Elev= 30
9530.613632.87329555.108 631.3859565.496628.66669586.273616.92479590.086616.3043
9638.215612.86569690.157613.18129710.934611.73469773.264610.05149813.417606.8574
9853.426606.22399903.438602.97269923.443599.11989933.445599.54279943.447598.9052
9963.452599.93279993.459596.685410023.47597.971410033.47600.145810043.47598.8671
10053.47598.828110073.48 604.11610083.48609.173910103.49625.481210113.49637.7466
10123.49654.185410133.49668.454510143.49675.2144 10153.5677.262710161.15678.0251
#Mann= 3 , 0 , 0
9530.613   0.056       09530.613   0.056       010161.15   0.056       0
#XS Ineff= 2 , 0
       0                               0
Bank Sta=9530.613,10161.15
Exp/Cntr=0.3,0.1

Type RM Length L Ch R = 1 ,7689.763,295.997700,295.997700,295.997700
XS GIS Cut Line= 6
571575.991512001807833.599548072571630.115661055807921.795258433
571654.373248488807984.004820392571698.158239394808218.862032607
571591.248966724808385.287807539571731.544655293808534.840611726
#Sta/Elev= 30
9465.715 671.7429515.732656.84849550.347648.94819572.842640.39649605.505636.6991
9626.651625.74649657.844 612.5959688.423610.27889708.559611.30519718.614614.2403
9749.142608.48739759.318609.01089840.745605.45419882.541 599.6619899.592598.7327
9918.198599.57559953.854596.3547 10010.6594.218710013.28594.295310025.17601.0457
10029.11602.178710060.82607.7343   10137611.447510166.23618.929910180.85 619.863
 10224.7 633.36310237.19649.959210239.31 651.78710250.91653.089110278.11 653.369
#Mann= 3 , 0 , 0
9465.715  0.0416       09465.715  0.0416       010278.11  0.0416       0
#XS Ineff= 2 , 0
       0                               0
Bank Sta=9465.715,10278.11
Exp/Cntr=0.3,0.1