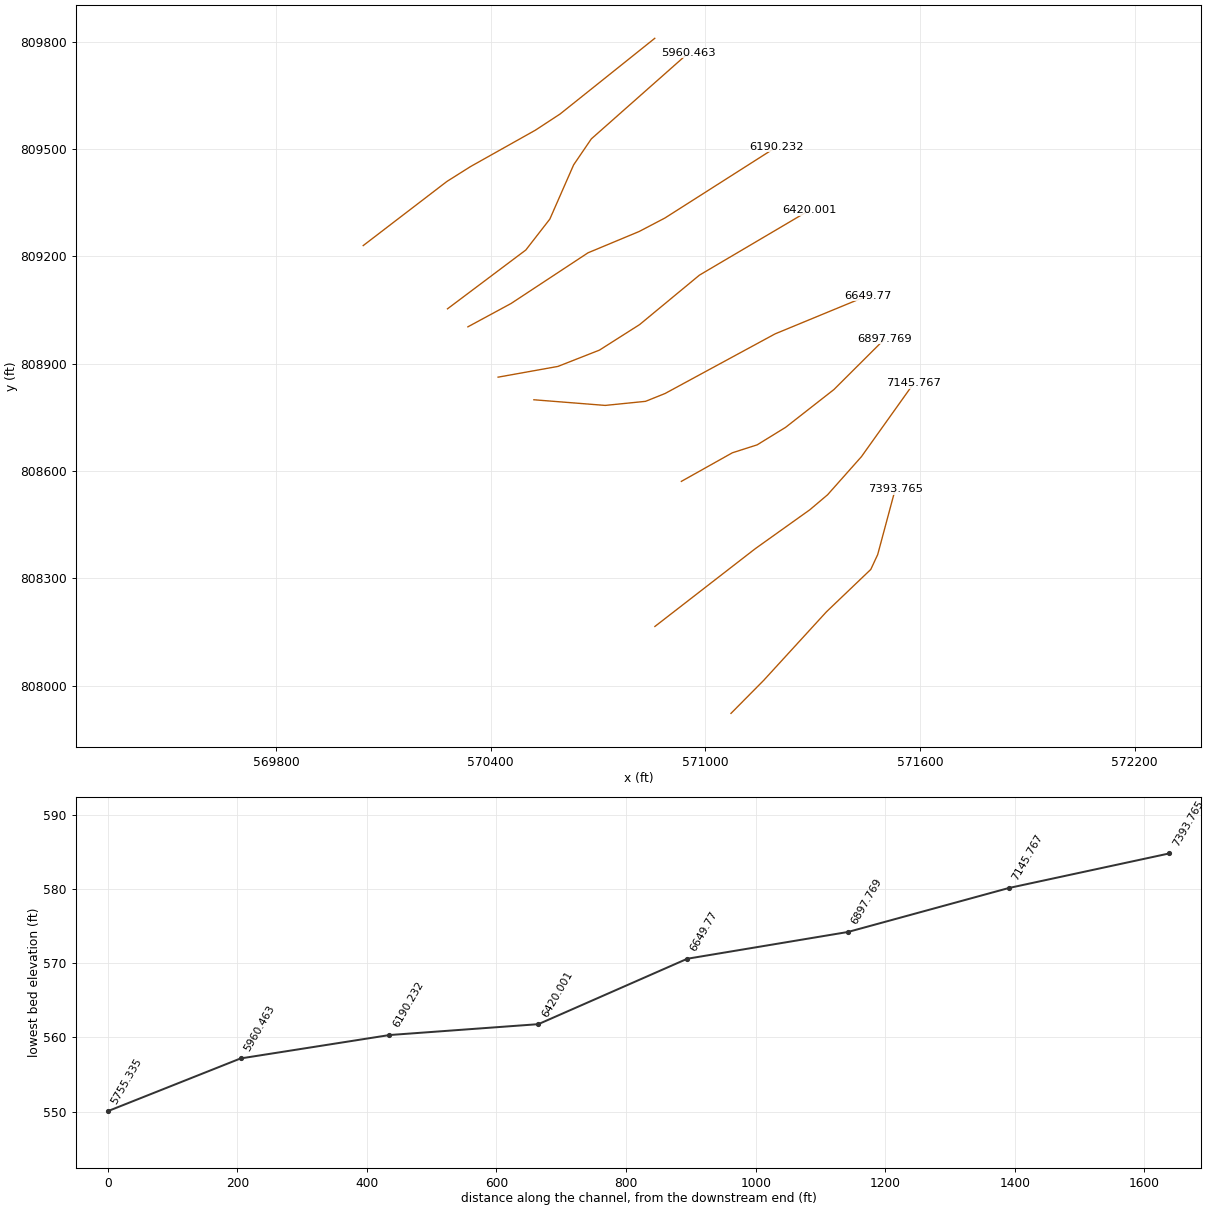
HEC-RAS study 11111_ras.prj: 11111

--- 11111_ras.g01 (geometry) --- (continued)

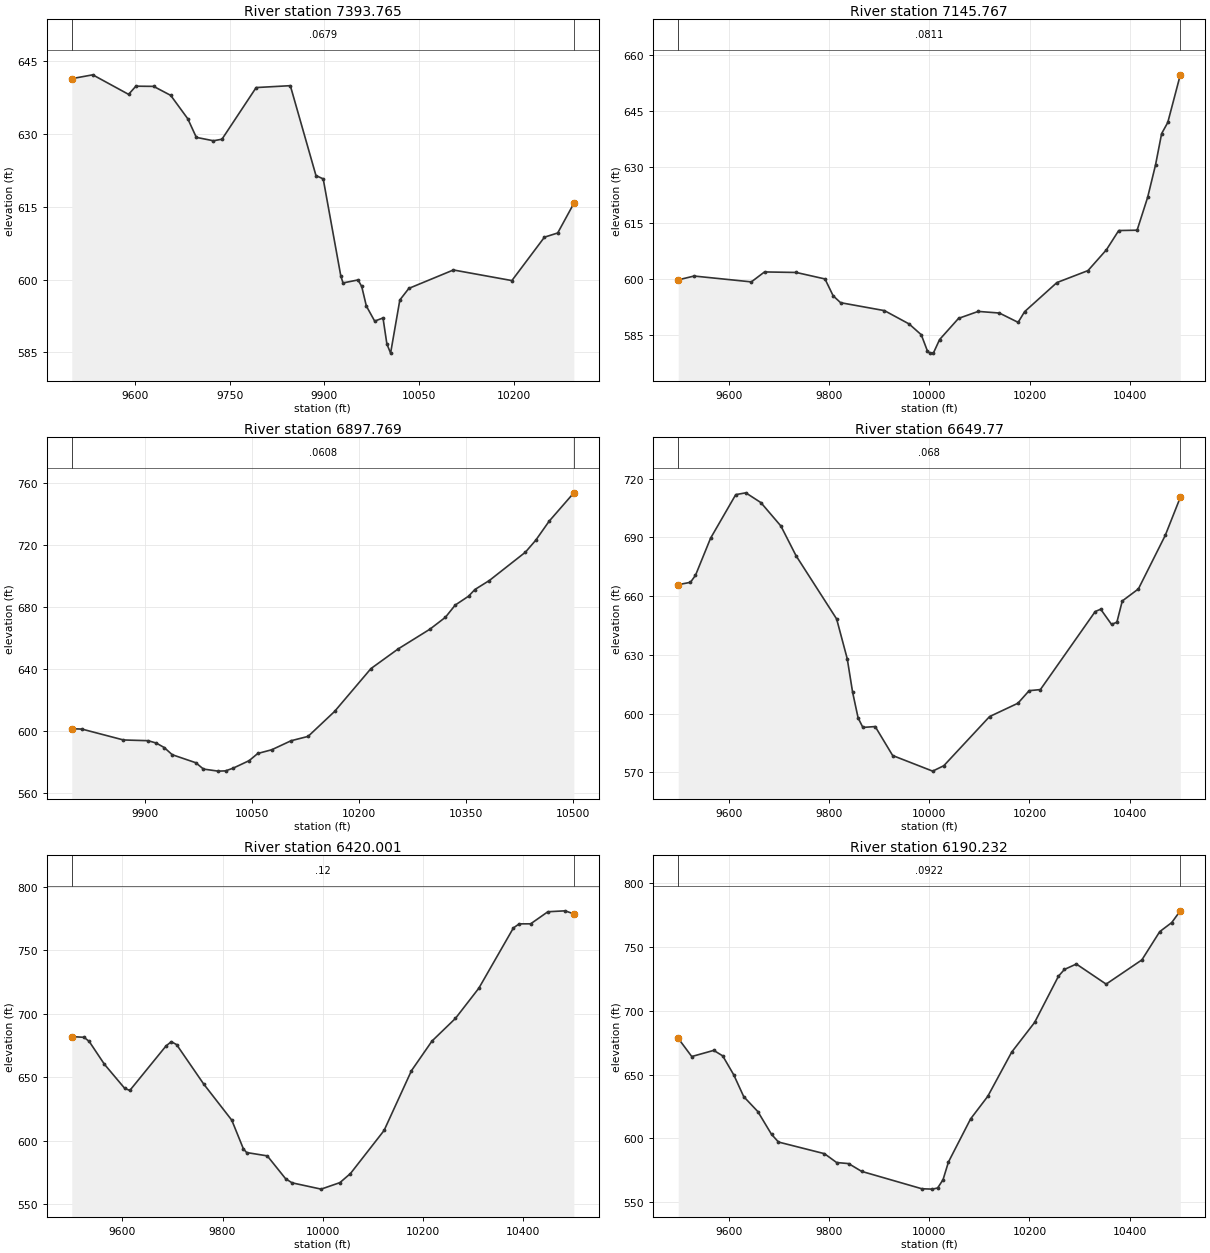
Type RM Length L Ch R = 1 ,7393.765,247.998400,247.998400,247.998400
XS GIS Cut Line= 6
 571071.56993103 807922.72511901571162.769901276 808014.85036236
 571338.43945232808206.723239437571462.226578295808324.998710707
571481.493224114808366.351648182571530.647348702808549.379279837
#Sta/Elev= 30
9499.038641.45349532.341 642.2459589.198638.21419600.738639.90379628.873639.8629
9655.989638.00889683.105633.18089696.664629.3424 9723.78628.64189737.338628.9609
9791.571639.61849845.803 640.0079886.478621.46549897.963620.77749925.852600.7761
9929.387599.30929953.185599.9325 9959.07598.58499966.404594.55139979.622591.4383
 9992.84592.0846    9999586.716210004.88584.832110019.54595.796310033.85598.1881
10104.56601.986110197.32599.7986   10249608.753810270.01609.619210295.62615.7228
#Mann= 3 , 0 , 0
9499.038  0.0679       09499.038  0.0679       010295.62  0.0679       0
#XS Ineff= 2 , 0
       0                10110.54       0
Bank Sta=9499.038,10295.62
Exp/Cntr=0.3,0.1

Type RM Length L Ch R = 1 ,7145.767,247.998500,247.998500,247.998500
XS GIS Cut Line= 6
570858.886713651808165.629861043571139.073062056808382.738831773
571292.128492191808491.953727852 571341.43239813808533.633399219
571436.121214256808640.225079953571582.550372863808845.476137369
#Sta/Elev= 30
9499.012599.74959530.636 600.776 9644.92599.21169671.206601.87399734.461601.7316
9791.857599.99469808.183595.48399823.016593.64729910.529591.5261 9959.75587.9588
9984.011585.07089996.142580.7762   10001580.159110008.31580.212510020.55583.7824
10058.37589.449810097.66591.315510139.83590.881410177.28 588.38810190.23591.2515
 10254.7599.031210316.67602.228710353.54607.809110378.01612.942710414.71613.0342
10435.73621.820610451.41630.459910463.64638.865910475.87641.836510500.92654.5842
#Mann= 3 , 0 , 0
9499.012  0.0811       09499.012  0.0811       010500.92  0.0811       0
#XS Ineff= 2 , 0
       09766.673        10157.93       0
Bank Sta=9499.012,10500.92
Exp/Cntr=0.3,0.1

Type RM Length L Ch R = 1 ,6897.769,247.998400,247.998400,247.998400
XS GIS Cut Line= 6
570932.845950029808571.133332424571075.421231136808651.030176895
571144.655387227808673.205162457571224.175498735808722.128584217
571359.195971831808827.758570452 571501.98159028 808970.01273639
#Sta/Elev= 30
9797.867601.52489812.054601.30389870.221594.2967 9904.64593.83269916.113592.3217
9927.326589.41549938.519584.81239971.608579.62129982.289575.550410002.86 574.234
10013.15574.394610023.89576.149710046.26580.987710058.28585.593510077.99588.0104
 10104.9593.788110128.79596.595410165.85612.644410216.78640.240610254.82652.8866
10299.29665.589410321.06673.269610334.82681.145610353.47686.846410362.36 691.156
10382.56696.941410433.04715.165110447.49722.839910466.24735.091710500.91753.3994
#Mann= 3 , 0 , 0
9797.867  0.0608       09797.867  0.0608       010500.91  0.0608       0
#XS Ineff= 2 , 0
       0                               0
Bank Sta=9797.867,10500.91
Exp/Cntr=0.3,0.1

Type RM Length L Ch R = 1 , 6649.77,229.768900,229.768900,229.768900
XS GIS Cut Line= 6
570520.700823468808799.196450447570720.147822942808783.415569162
 570832.81077962 808794.82821026570887.498806755808816.806387004
571194.883459787 808983.40397674571453.034292742809089.901860947
#Sta/Elev= 30
9499.097665.8116 9523.49 667.0229533.529670.59579563.645689.54549613.839711.7859
9633.916712.70719663.974707.73449704.038695.73469734.042680.66079815.152648.3175
9836.349627.98019847.021610.94479858.053597.74449867.564592.9293 9892.16593.3798
9926.989578.582110006.78570.620910029.03 573.381 10120.3598.464210176.92  605.28
10199.33   611.710221.75612.252910331.17652.107710342.11653.2885 10363.7645.5329
10374.42646.662810385.14657.4975 10417.3663.6368 10470.9690.973710500.96710.4039
#Mann= 3 , 0 , 0
9499.097   0.068       09499.097   0.068       010500.96   0.068       0
#XS Ineff= 2 , 0
       0                               0
Bank Sta=9499.097,10500.96
Exp/Cntr=0.3,0.1

Type RM Length L Ch R = 1 ,6420.001,229.769000,229.769000,229.769000
XS GIS Cut Line= 6
570420.589962238808862.369778167570587.849675046808892.391918879
 570704.04526937808938.031654812570816.192264093809009.346711725
570983.462155308809147.598141294 571290.20263701809328.468873037
#Sta/Elev= 30
 9499.15681.92289523.817 681.3399533.923678.09639564.239660.14569604.733641.1712
9614.993639.51179687.268674.57749697.794677.90179708.319675.60159762.382644.5595
9818.444616.08779841.559593.54559848.017590.61789889.292587.97839925.785570.0182
9938.582566.7683 9996.69561.7971 10034.1566.9109 10055.2 574.058 10122.3607.9821
10176.92655.053610217.93678.413410264.68696.232510311.42720.047610380.36767.4807
10391.82770.674110414.75770.716710449.14 780.22210483.53780.950310500.96778.5304
#Mann= 3 , 0 , 0
 9499.15    0.12       0 9499.15    0.12       010500.96    0.12       0
#XS Ineff= 2 , 0
       0                               0
Bank Sta=9499.15,10500.96
Exp/Cntr=0.3,0.1

Type RM Length L Ch R = 1 ,6190.232,229.768900,229.768900,229.768900
XS GIS Cut Line= 6
570336.232894284809003.067595585570456.777865755 809068.19974282
570671.966079639 809209.92946323570814.765600644809269.412618432
570886.969570704809307.218438472571199.515873335809506.277202278
#Sta/Elev= 30
9499.106678.28969526.083664.0713 9569.97668.88479587.914664.57059609.866649.7525
9629.814632.68359657.961620.99899685.209603.22549699.174597.17019790.862588.0585
9815.152 581.1429839.074580.3037 9865.07574.2179 9985.16560.623510006.24560.3293
10016.72561.226710027.49 567.69510038.31581.5616 10082.5615.278710116.73632.9203
10164.48667.522210210.29690.773710257.84726.928810269.73732.209510293.51736.4445
10352.95720.725610424.27739.675610459.94761.806110483.71768.826810500.97778.0701
#Mann= 3 , 0 , 0
9499.106  0.0922       09499.106  0.0922       010500.97  0.0922       0
#XS Ineff= 2 , 0
       0                               0
Bank Sta=9499.106,10500.97
Exp/Cntr=0.3,0.1

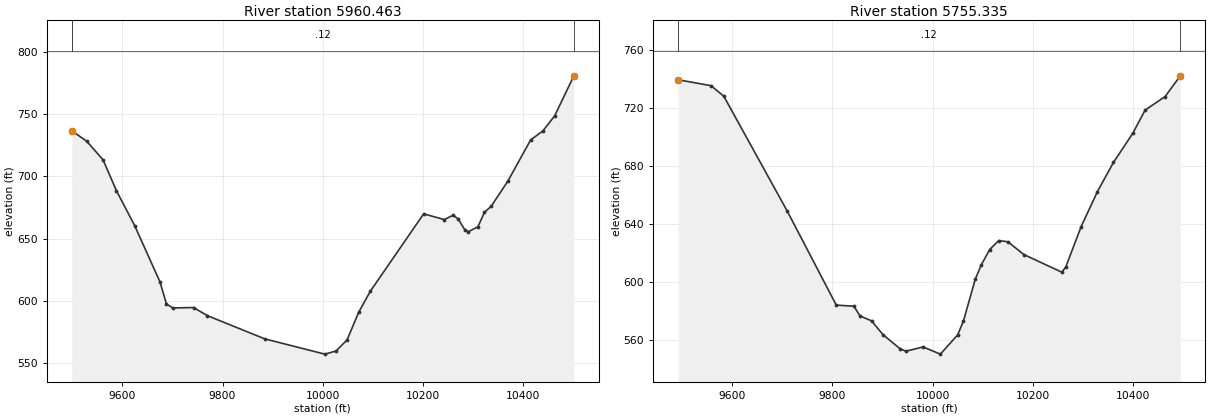
Type RM Length L Ch R = 1 ,5960.463,205.128600,205.128600,205.128600
XS GIS Cut Line= 6
570279.189610161 809053.38021579570498.143860072809217.790182062
570565.250679013809304.171807598570631.763285715809455.749855587
570681.097623734 809528.21890259570953.185391359809768.915016318
#Sta/Elev= 30
9499.181736.66759529.099728.2503 9561.56713.34779588.306688.49499624.706660.4336
 9675.26615.1597 9688.06597.48499700.965594.2696 9742.16594.61759769.623588.1218
9884.436569.404910004.07 557.17310026.28559.656410048.49 568.62410071.81591.0182
10095.18607.923410201.26669.927210242.54665.301710259.63668.7541   10270665.9523
10283.17657.219310289.84655.431510309.47659.507310322.63671.164210336.01 676.013
10369.53696.397610414.67729.318310439.16736.567610462.66 748.70210500.91780.8462
#Mann= 3 , 0 , 0
9499.181    0.12       09499.181    0.12       010500.91    0.12       0
#XS Ineff= 2 , 0
       0                               0
Bank Sta=9499.181,10500.91
Exp/Cntr=0.3,0.1

Type RM Length L Ch R = 1 ,5755.335,0.000000,0.000000,0.000000
XS GIS Cut Line= 6
570043.643060094809230.136751613570277.905279725809409.570877442
570343.600480546809450.943563598570525.116605992809552.800082875
570594.116084406809598.002232412570858.498199418809809.347027894
#Sta/Elev= 30
9492.222739.5822 9557.61735.52399583.075728.27359709.821648.81179807.569583.9316
9843.023583.1187 9854.84576.46069878.031573.03559900.887563.45749935.367553.6506
9946.598552.07069980.881555.007710015.34550.050910049.95563.409210061.48573.0389
10084.97601.817710096.92611.661410113.66622.298810131.91628.530510150.16627.6602
10181.93618.843110257.57606.683910265.44  610.1110296.25 638.15410328.82662.4016
10360.71682.453510399.39702.667710423.88718.624710463.85728.015510494.15742.3255
#Mann= 3 , 0 , 0
9492.222    0.12       09492.222    0.12       010494.15    0.12       0
#XS Ineff= 2 , 0
       0                               0
Bank Sta=9492.222,10494.15
Exp/Cntr=0.3,0.1